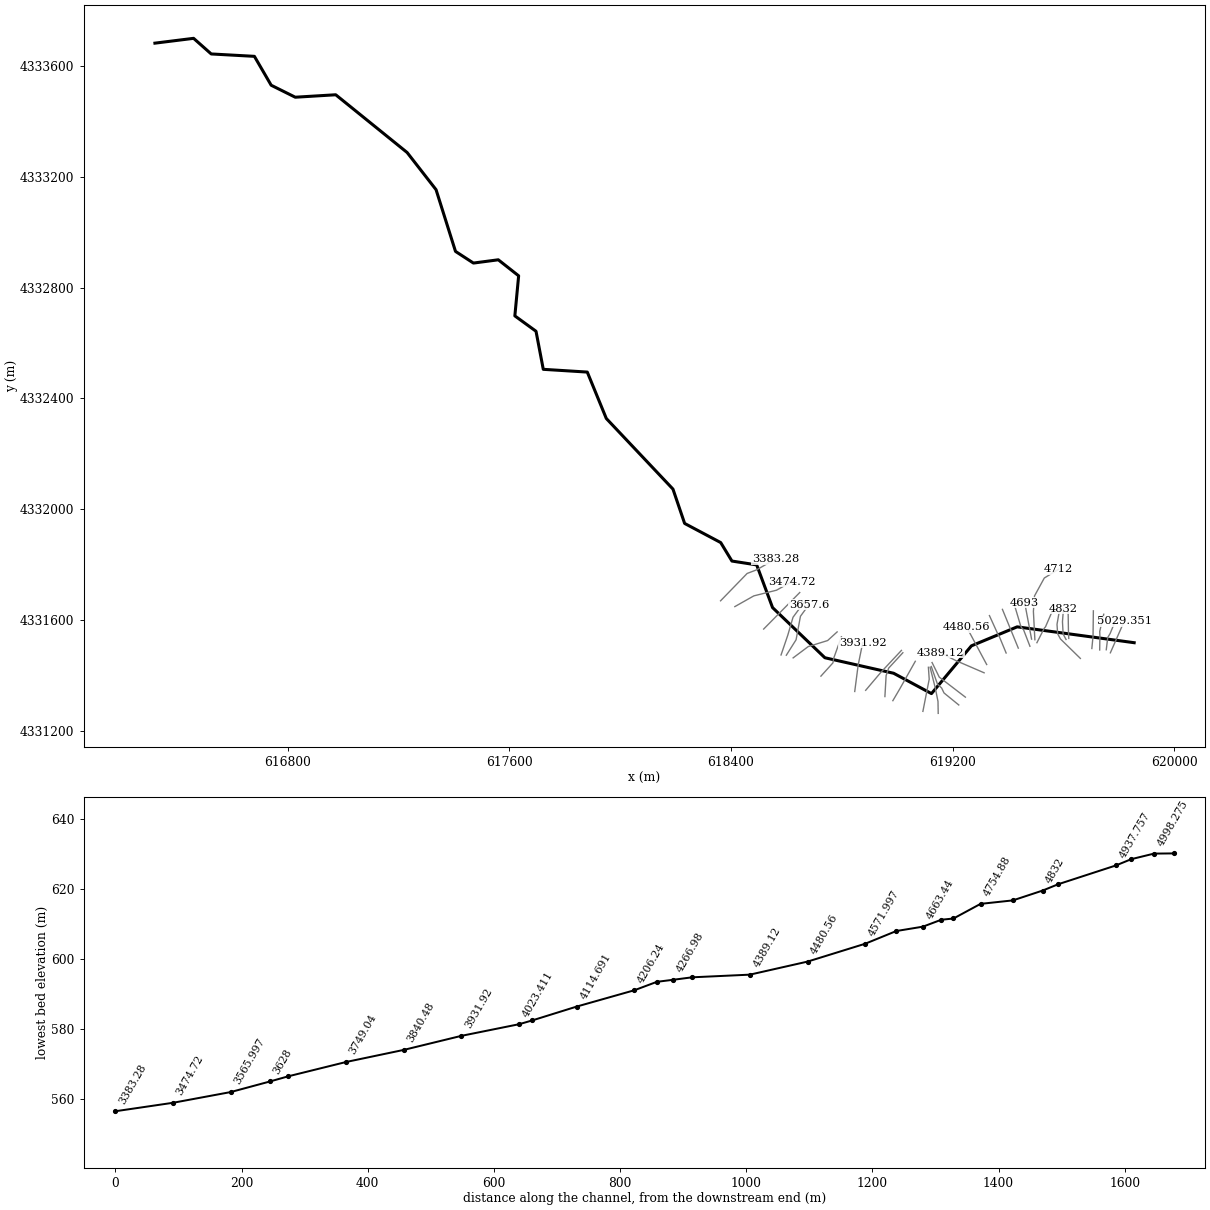
--- MillRun.prj (project) ---

Proj Title=MillRun
Current Plan=p01
Default Exp/Contr=0.3,0.1
SI Units
Geom File=g01
Flow File=f01
Plan File=p01
Background Map Layer=Google Hybrid
Y Axis Title=Elevation
X Axis Title(PF)=Main Channel Distance
X Axis Title(XS)=Station
BEGIN DESCRIPTION:
September 2018
Tucker County ABFE Study
US Army Corps of Engineers, Pittsburgh District
NAD 1983 UTM 17N (meters)
END DESCRIPTION:
DSS Export Rating Curves= 0
DSS Export Rating Curve Sorted= 0
DSS Export Volume Flow Curves= 0
DXF OffsetX= 0
DXF OffsetY= 0
DXF ScaleX= 1
DXF ScaleY= 10

--- MillRun.p01 (plan) ---

Plan Title=MillRun_plan
Program Version=5.05
Short Identifier=Plan1_subcritical
Geom File=g01
Flow File=f01
Subcritical Flow
K Sum by GR= 0
Std Step Tol= 0.003
Critical Tol= 0.003
Num of Std Step Trials= 20
Max Error Tol= 0.1
Flow Tol Ratio= 0.001
Split Flow NTrial= 30
Split Flow Tol= 0.006
Split Flow Ratio= 0.02
Log Output Level= 0
Friction Slope Method= 1
Unsteady Friction Slope Method= 2
Unsteady Bridges Friction Slope Method= 1
Parabolic Critical Depth
Global Vel Dist= 0 , 0 , 0
Global Log Level= 0
CheckData=True
Encroach Param=-1 ,0,0, 0
Computation Interval=1MIN
Output Interval=1HOUR
Instantaneous Interval=1HOUR
Mapping Interval=1HOUR
Computation Time Step Use Courant=        0
Computation Time Step Use Time Series=    0
Computation Time Step Count To Double=0
Computation Time Step Max Doubling=0
Computation Time Step Max Halving=0
Computation Time Step Residence Courant=0
Run HTab= 0
Run UNet= 0
Run Sediment= 0
Run PostProcess= 0
Run WQNet= 0
Run RASMapper=-1
UNET Theta= 1
UNET Theta Warmup= 1
UNET ZTol= 0.006
UNET ZSATol= 0.006
UNET MxIter= 20
UNET Max Iter WO Improvement= 0
UNET MaxInSteps= 0
UNET DtIC= 0
UNET DtMin= 0
UNET MaxCRTS= 20
UNET WFStab= 2
UNET SFStab= 1
UNET WFX= 1
UNET SFX= 1
UNET 1D Methodology=Finite Difference
UNET DSS MLevel= 4
UNET Pardiso=0
UNET DZMax Abort= 30
UNET Use Existing IB Tables=-1
UNET Froude Reduction=False
UNET Froude Limit= 0.8
UNET Froude Power= 4
UNET D1 Cores= 0
UNET D2 Coriolis=0
UNET D2 Cores= 0
UNET D2 Theta= 1
UNET D2 Theta Warmup= 1
UNET D2 Z Tol= 0.003
UNET D2 Volume Tol= 0.003
UNET D2 Max Iterations= 20
UNET D2 Equation= 0
UNET D2 RampUpFraction=0.1
UNET D2 TimeSlices= 1
UNET D2 BCVolumeCheck=0
UNET D1D2 MaxIter= 0
UNET D1D2 ZTol=0.003
UNET D1D2 QTol=0.1
UNET D1D2 MinQTol=0.03
Write IC File= 0
Write IC File at Fixed DateTime=0
Write IC File at Sim End=0
Echo Input=False
Echo Parameters=False
Echo Output=False
Write Detailed= 0
HDF Write Warmup=0
HDF Write Time Slices=0
HDF Flush=0
HDF Face Node Velocities=0
HDF Compression= 1
HDF Chunk Size= 1
HDF Spatial Parts= 1
HDF Use Max Rows=0
HDF Fixed Rows= 1
Calibration Method= 0
Calibration Iterations= 20
Calibration Max Change=0.05
Calibration Tolerance=0.2
Calibration Maximum=1.5
Calibration Minimum=0.5
Calibration Optimization Method= 1
WQ AD Non Conservative
WQ ULTIMATE=-1
WQ Max Comp Step=1HOUR
WQ Output Interval=15MIN
WQ Output Selected Increments= 0
WQ Output face flow=0
WQ Output face velocity=0
WQ Output face area=0
WQ Output face dispersion=0
WQ Output cell volume=0
WQ Output cell surface area=0
WQ Output cell continuity=0
WQ Output cumulative cell continuity=0
WQ Output face conc=0
WQ Output face dconc_dx=0
WQ Output face courant=0
WQ Output face peclet=0
WQ Output face adv mass=0
WQ Output face disp mass=0
WQ Output cell mass=0
WQ Output cell source sink temp=0
WQ Output nsm pathways=0
WQ Output nsm derived pathways=0
WQ Output MaxMinRange=-1
WQ Daily Max Min Mean=-1
WQ Daily Range=0
WQ Daily Time=0
WQ Create Restart=0
WQ Fixed Restart=0
WQ System Summary=0
WQ Write To DSS=0
WQ Use Fixed Temperature=0
Sorting and Armoring Iterations= 10
XS Update Threshold= 0.02
Bed Roughness Predictor= 0
Hydraulics Update Threshold= 0.02
Energy Slope Method= 1
Volume Change Method= 1
Sediment Retention Method= 0
XS Weighting Method= 0
Number of US Weighted Cross Sections= 1
Number of DS Weighted Cross Sections= 1
Upstream XS Weight=0
Main XS Weight=1
Downstream XS Weight=0
Number of DS XS's Weighted with US Boundary= 1
Upstream Boundary Weight= 1
Weight of XSs Associated with US Boundary= 0
Number of US XS's Weighted with DS Boundary= 1
Downstream Boundary Weight= 0.5
Weight of XSs Associated with DS Boundary= 0.5
Percentile Method= 0
Sediment Output Level= 4
Mass or Volume Output= 0
Output Increment Type= 1
Profile and TS Output Increment= 1
XS Output Flag= 0
XS Output Increment= 10
Write Gradation File= 0
Read Gradation Hotstart= 0
Write HDF5 File= 1
Write Binary Output= 1
Write DSS Sediment File= 0
SV Curve= 0
Specific Gage Flag= 0

--- MillRun.f01 (steady flow) ---

Flow Title=MillRun_flow
Program Version=5.05
Number of Profiles= 1
Profile Names=PF 1
River Rch & RM=Mill Run (Cheat),1               ,5029.351
   14.64
River Rch & RM=Mill Run (Cheat),1               ,4754.88
 16.5652
River Rch & RM=Mill Run (Cheat),1               ,4023.411
 26.5043
River Rch & RM=Mill Run (Cheat),1               ,2742.766
 28.4582
River Rch & RM=Mill Run (Cheat),1               ,1920.24
 31.4314
River Rch & RM=Mill Run (Cheat),1               ,182.88
 33.8383
Boundary for River Rch & Prof#=Mill Run (Cheat),1               , 1
Up Type= 2
Dn Type= 1
Dn Known WS=480
DSS Import GetInterval= 0
DSS Import GetPeak= 0
DSS Import FillOption= 0

--- MillRun.g01 (geometry) ---

Geom Title=MillRun_geometry
Program Version=5.05

River Reach=Mill Run (Cheat),1
Reach XY= 30
     619854.5323    4331518.6278     619432.3595    4331575.8314
     619267.2592     4331507.238     619123.1933    4331334.9939
      618986.668    4331408.4159     618738.6206    4331464.3754
     618549.8307    4331645.2906     618492.5576    4331799.3386
     618403.2606    4331813.2292     618362.7793    4331879.9043
      618232.604    4331948.9607     618190.5352     4332072.786
     617950.0284    4332327.5802     617881.3689    4332495.0618
     617722.6186    4332504.9837     617696.4248    4332642.3027
     617620.0487    4332697.7902     617633.7184    4332842.3281
     617560.2965    4332900.1728     617470.6025    4332888.3657
     617405.9117    4332930.4346      617335.767    4333153.0896
     617231.3887    4333287.2336     616973.7836    4333495.5721
616827.795204374   4333486.72289616740.888005631  4333529.976055
      616680.355    4333634.2164     616524.5529    4333642.8343
     616460.9505     4333699.183     616321.4041    4333681.7894

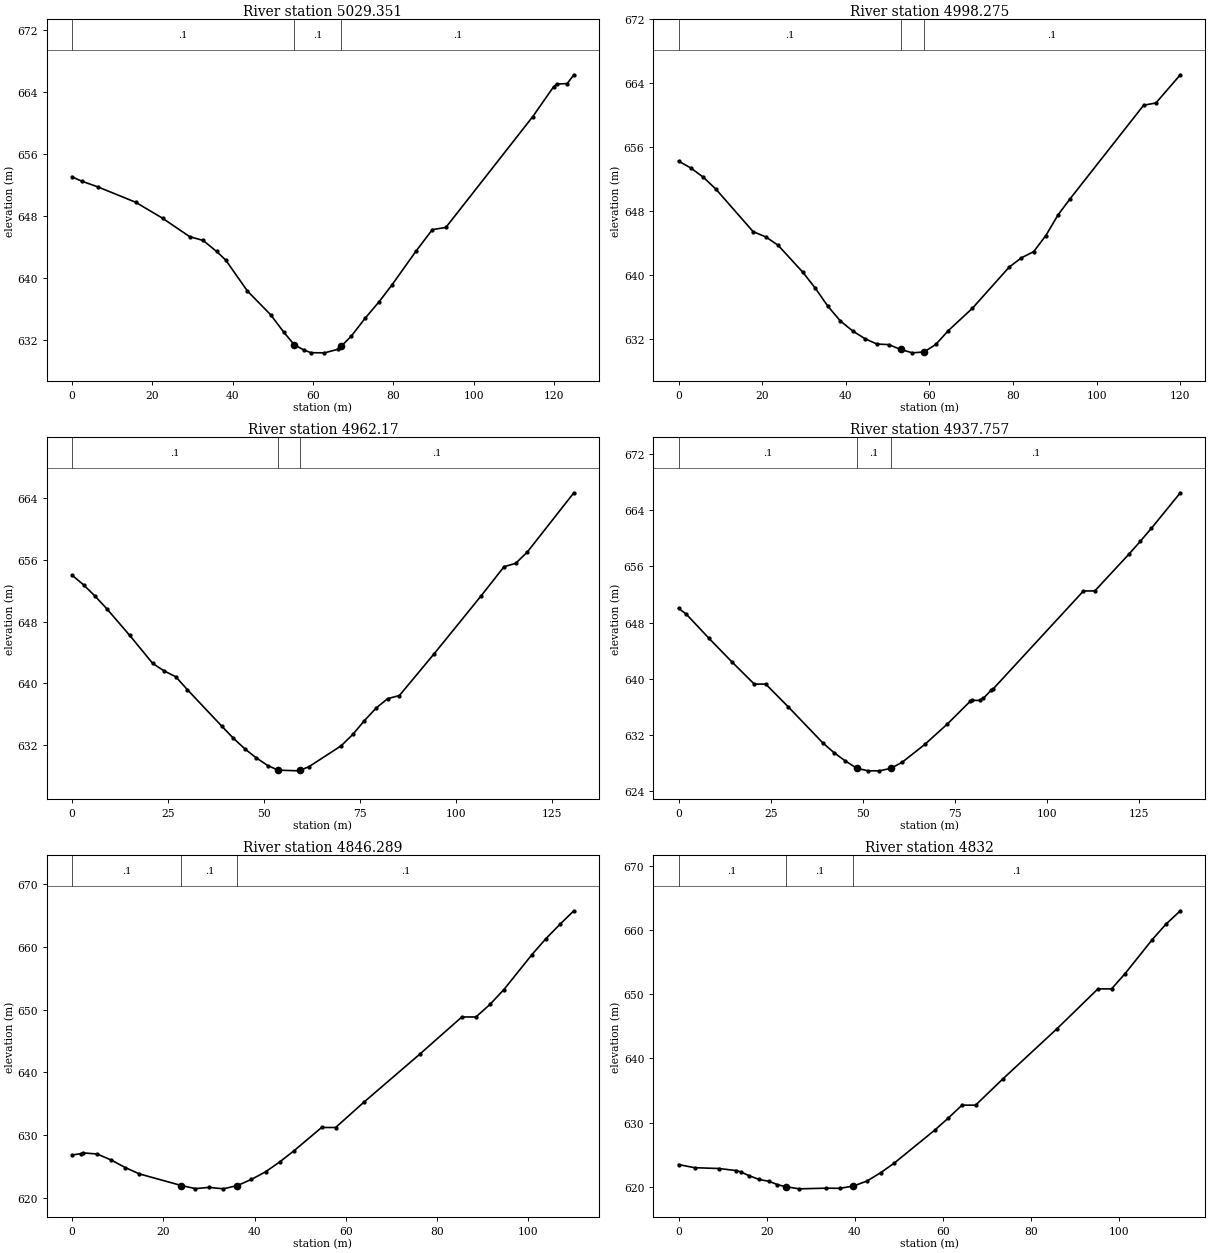
Type RM Length L Ch R = 1 ,5029.351,32.87,31.08,30.36
XS GIS Cut Line= 2
619768.6195260044331482.06569371     619818.8339    4331596.4657
#Sta/Elev= 30
       0     653   2.411 652.443   6.334 651.726   15.84 649.723  22.555 647.653
   29.27 645.287  32.627 644.798  35.984 643.375   38.22 642.287  43.666 638.269
  49.414 635.224  52.771 632.923   55.36  631.31  57.666 630.676  59.486 630.311
  62.844 630.294  66.201 630.753  66.999 631.138  69.558 632.472  72.916 634.727
  76.465 636.899   79.63 639.047  85.665 643.438  89.703   646.2   93.06 646.468
  114.71 660.781 119.919 664.648 120.663 664.975 123.277 665.038 124.935 666.173
#Mann= 3 , 0 , 0
       0      .1       0   55.36      .1       0  66.999      .1       0
Bank Sta=55.36,66.999
XS Rating Curve= 0 ,0
Exp/Cntr=0.3,0.1

Type RM Length L Ch R = 1 ,4998.275,27.47,36.1,38.36
XS GIS Cut Line= 4
     619753.8763     4331493.169      619759.168    4331537.4868
     619767.8993    4331551.9331     619789.9656     4331606.067
#Sta/Elev= 30
       0  654.24    2.98  653.36    5.95  652.21    8.93  650.73   17.85   645.4
   20.83  644.76    23.8  643.71   29.76   640.3   32.73  638.31   35.71  636.07
   38.68  634.23   41.66  632.97   44.63  631.99   47.45  631.34   50.26  631.27
   53.07  630.67   55.89  630.24    58.7  630.35   61.51  631.29   64.44  632.99
   70.28  635.83   79.05  640.97   81.97  642.13    84.9   642.9   87.82  644.92
   90.74  647.51   93.66  649.55   111.2  661.23  114.13  661.51  119.97  665.04
#Mann= 3 , 0 , 0
       0      .1       0   53.07      .1       0    58.7      .1       0
Bank Sta=53.07,58.7
XS Rating Curve= 0 ,0
Exp/Cntr=0.3,0.1

Type RM Length L Ch R = 1 ,4962.17 ,26.07,24.41,24.15
XS GIS Cut Line= 4
     619730.1167    4331492.4017     619730.9105    4331543.3606
     619730.2754    4331559.3944     619744.7217     4331621.307
#Sta/Elev= 30
       0  654.02       3  652.77       6   651.3    8.99   649.7   14.99  646.22
   20.99  642.58   23.98   641.6   26.98  640.86   29.98  639.19   38.97  634.44
   41.97  632.88   44.97   631.5   47.97  630.32   50.97  629.32   53.64  628.74
   58.99  628.65   59.35  628.73   61.66  629.19   70.04   631.9   73.07  633.38
   76.09  635.16   79.12  636.79   82.15  638.02   85.18  638.41   94.26  643.85
  106.37  651.29  112.42  655.12  115.45  655.56  118.48  657.03  130.59  664.71
#Mann= 3 , 0 , 0
       0      .1       0   53.64      .1       0   59.35      .1       0
Bank Sta=53.64,59.35
XS Rating Curve= 0 ,0
Exp/Cntr=0.3,0.1

Type RM Length L Ch R = 1 ,4937.757,91.37,91.47,92.35
XS GIS Cut Line= 3
619701.8472020614331497.63091147     619706.1499    4331542.4544
     619707.3118    4331633.5075
#Sta/Elev= 29
       0 650.021   2.023 649.241     8.2 645.787  14.376 642.446  20.553  639.22
  23.642 639.228  29.818 635.947  39.084 630.863  42.172 629.438  45.259 628.255
  48.334 627.221  51.408 626.851  54.483 626.853  57.557 627.199  60.632 628.068
  66.781 630.614   72.93 633.542  79.079 636.756  79.612 636.903  81.646 636.899
  82.648 637.171   84.76 638.347  85.228 638.479 109.824  652.51 112.899 652.515
 122.122 657.744 125.197  659.57 128.271 661.467  136.09 666.516
#Mann= 3 , 0 , 0
       0      .1       0  48.334      .1       0  57.557      .1       0
Bank Sta=48.334,57.557
XS Rating Curve= 0 ,0
Exp/Cntr=0.3,0.1

Type RM Length L Ch R = 1 ,4846.289,24.7,24.7,24.7
XS GIS Cut Line= 3
619618.571457285 4331534.1230604     619617.4505    4331558.9309
     619616.0304    4331644.0908
#Sta/Elev= 28
       0 626.864   1.899 627.073   2.415 627.199   5.492 627.022    8.57 626.066
  11.647 624.869  14.725 623.862  23.957 622.009  27.032 621.519  30.107 621.715
  33.182 621.482  36.256 622.012  39.331 622.987  42.406 624.187  45.481 625.739
  48.555 627.476  54.705 631.237  57.779 631.236  63.929 635.233  76.228   642.9
  85.452 648.813  88.526 648.813  91.601 650.796  94.676 653.175 100.825 658.736
   103.9 661.283 106.975 663.563 110.005 665.699
#Mann= 3 , 0 , 0
       0      .1       0  23.957      .1       0  36.256      .1       0
Bank Sta=23.957,36.256
XS Rating Curve= 0 ,0
Exp/Cntr=0.3,0.1

Type RM Length L Ch R = 1 ,4832    ,47.2,47.2,47.2
XS GIS Cut Line= 4
619608.7417068044331530.25324127619598.2422646224331550.05218938
619595.8423921234331594.44983061619599.4422008724331641.24734434
#Sta/Elev= 29
       0  623.45   3.631 622.965    9.19 622.834  13.111 622.513  14.071 622.318
  16.012 621.716  18.286 621.132   20.56 620.833  22.411 620.329  24.268 620.007
  27.347 619.669  33.504 619.773  36.583  619.75  39.662 620.103  42.741 620.885
  45.819 622.172  48.898 623.664  58.134 628.833  61.213 630.717  64.292 632.711
  67.371 632.705  73.629 636.846  85.872 644.642  95.122 650.828  98.205 650.824
 101.288 653.214 107.455 658.518 110.538 660.904 113.809 662.998
#Mann= 3 , 0 , 0
       0      .1       0  24.268      .1       0  39.662      .1       0
Bank Sta=24.268,39.662
XS Rating Curve= 0 ,0
Exp/Cntr(USF)=0,0
Exp/Cntr=0.3,0.1

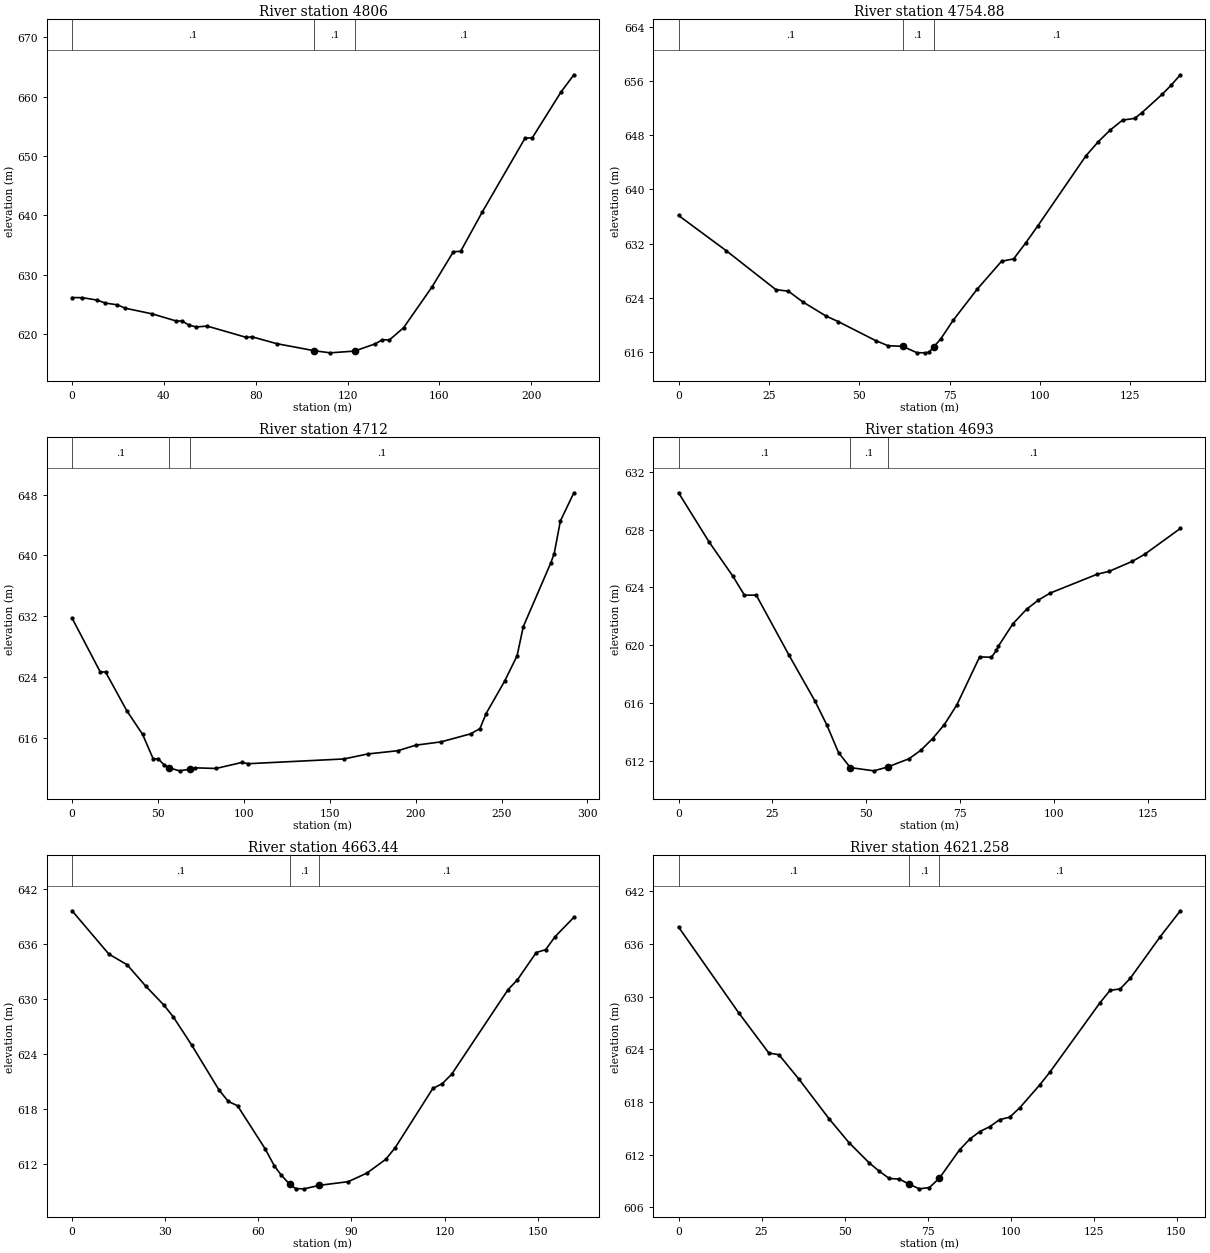
Type RM Length L Ch R = 1 ,4806    ,51.2,51.2,51.2
XS GIS Cut Line= 5
619660.4167667964331461.93257894619588.6005822694331532.12884953
619578.3411273374331551.02784546619576.1812420884331585.04603813
619586.9806683334331646.60276773
#Sta/Elev= 30
       0 626.168   4.508 626.149   11.03 625.738  14.368  625.25  19.726 624.945
  23.165 624.376  34.944 623.418  45.155 622.245  47.988 622.204  50.757 621.562
  53.951  621.22  58.858 621.363  75.942 619.458  78.424 619.554  89.136 618.405
 105.439 617.222 112.435 616.861 123.074 617.159 132.051 618.385 135.131 619.066
 138.212 619.036 144.373 621.092 156.704 627.939 166.067 633.901 169.189 633.939
 178.552 640.522  197.28 653.025 200.401 653.069 212.886 660.762 218.512 663.685
#Mann= 3 , 0 , 0
       0      .1       0 105.439      .1       0 123.074      .1       0
Bank Sta=105.439,123.074
XS Rating Curve= 0 ,0
Exp/Cntr(USF)=0,0
Exp/Cntr=0.3,0.1

Type RM Length L Ch R = 1 ,4754.88 ,42.9,42.9,42.9
XS GIS Cut Line= 4
619503.6577704014331518.65801802     619529.9103    4331570.4373
     619534.6847    4331576.0423     619563.7751    4331643.4294
#Sta/Elev= 30
       0 636.154   13.15 630.969  26.938 625.196  30.385 624.976  34.306 623.413
  40.725 621.326  44.172 620.482  54.512 617.681  57.959 616.918  61.981  616.83
  65.917 615.892  68.318 615.867  69.265 615.964  70.657 616.761  72.614 617.981
  75.962 620.663  82.659 625.296  89.356 629.387  92.705 629.744  96.053 632.106
  99.402 634.629 112.665 644.937 116.144 647.066 119.493 648.802 122.841 650.237
  126.19  650.49 128.178 651.327 133.806 654.058 136.235 655.364 138.815  656.93
#Mann= 3 , 0 , 0
       0      .1       0  61.981      .1       0  70.657      .1       0
Bank Sta=61.981,70.657
XS Rating Curve= 0 ,0
Exp/Cntr=0.3,0.1

Type RM Length L Ch R = 1 ,4712    ,19.4,19.4,19.4
XS GIS Cut Line= 5
619496.3010652714331529.35976404619490.9680152744331631.35434524
619494.9678027714331687.35137021619530.2992590044331752.01460143
619581.6298652284331783.34627016
#Sta/Elev= 30
       0 631.759  16.421  624.68    19.5 624.682  31.813 619.603  41.049 616.479
  47.206 613.264  50.284 613.249  53.363 612.507  56.441 612.077  62.598 611.684
  68.755 611.911  71.834 612.077  83.798 611.997  98.758 612.782 102.619 612.622
 158.274 613.247 172.086 613.903 189.602 614.328 200.111 615.059 214.803 615.494
  231.96 616.544 237.426 617.236 241.028  619.22 251.833 623.489 259.037 626.804
 262.638 630.631 278.628 638.998 280.647 640.242 284.249 644.531 292.097  648.24
#Mann= 3 , 0 , 0
       0      .1       0  56.441      .1       0  68.755      .1       0
Bank Sta=56.441,68.755
XS Rating Curve= 0 ,0
Exp/Cntr(USF)=0,0
Exp/Cntr=0.3,0.1

Type RM Length L Ch R = 1 ,4693    ,29.1,29.1,29.1
XS GIS Cut Line= 2
619484.3861190084331531.58887822619459.5474386464331662.80190709
#Sta/Elev= 30
       0 630.547   8.163 627.136  14.421 624.794   17.55 623.465  20.679 623.473
  29.352 619.341  36.323  616.14  39.452 614.501  42.581 612.585   45.71 611.548
  51.968 611.323   55.66 611.589  61.354 612.162  64.483 612.743  67.612 613.552
  70.741 614.519  74.076 615.886  80.127 619.199  83.256 619.177  84.599 619.645
  85.146 619.955  89.005 621.496  92.643 622.499  95.772  623.13  98.901 623.612
 111.416 624.917 114.545  625.11 120.803 625.812 124.062 626.296 133.543 628.079
#Mann= 3 , 0 , 0
       0      .1       0   45.71      .1       0   55.66      .1       0
Bank Sta=45.71,55.66
XS Rating Curve= 0 ,0
Exp/Cntr(USF)=0,0
Exp/Cntr=0.3,0.1

Type RM Length L Ch R = 1 ,4663.44 ,46.38,42.18,40.46
XS GIS Cut Line= 5
     619478.4468    4331505.8458      619454.955    4331566.6138
     619449.4642     4331570.749     619444.6556     4331580.512
     619422.2227    4331655.9971
#Sta/Elev= 30
       0   639.6   11.85  634.89   17.77  633.72   23.69  631.42   29.61  629.33
   32.58  628.07    38.5  625.01   47.38  620.08   50.34  618.86   53.31  618.39
   62.19  613.71   65.15  611.86   67.44  610.82   70.06  609.87   72.02  609.37
   74.75  609.35   79.64  609.73   88.96  610.13   95.02  611.07  101.08  612.57
  104.11  613.83  116.22  620.27  119.25  620.79  122.28  621.81  140.45  631.02
  143.48  632.09  149.54  635.06  152.57  635.37   155.6  636.78  161.66  638.89
#Mann= 3 , 0 , 0
       0      .1       0   70.06      .1       0   79.64      .1       0
Bank Sta=70.06,79.64
XS Rating Curve= 0 ,0
Exp/Cntr=0.3,0.1

Type RM Length L Ch R = 1 ,4621.258,47.74,49.26,49.43
XS GIS Cut Line= 2
     619436.4418    4331499.0163     619379.2256    4331638.9151
#Sta/Elev= 30
       0  637.95   18.14  628.16   27.21  623.58   30.23  623.39   36.28   620.6
   45.34  616.09   51.39  613.35   57.44  611.06   60.46  610.11   63.48  609.28
    66.5  609.21   69.53  608.62   72.55   608.1   75.57  608.25    78.6  609.33
   84.64  612.54   87.67  613.75   90.69  614.62   93.71  615.18   96.73  615.99
   99.76  616.27  102.78  617.34  108.83  619.96  111.85   621.4  126.96  629.32
  129.99  630.73  133.01  630.89  136.03  632.08   145.1  636.85  151.15   639.8
#Mann= 3 , 0 , 0
       0      .1       0   69.53      .1       0    78.6      .1       0
Bank Sta=69.53,78.6
XS Rating Curve= 0 ,0
Exp/Cntr=0.3,0.1

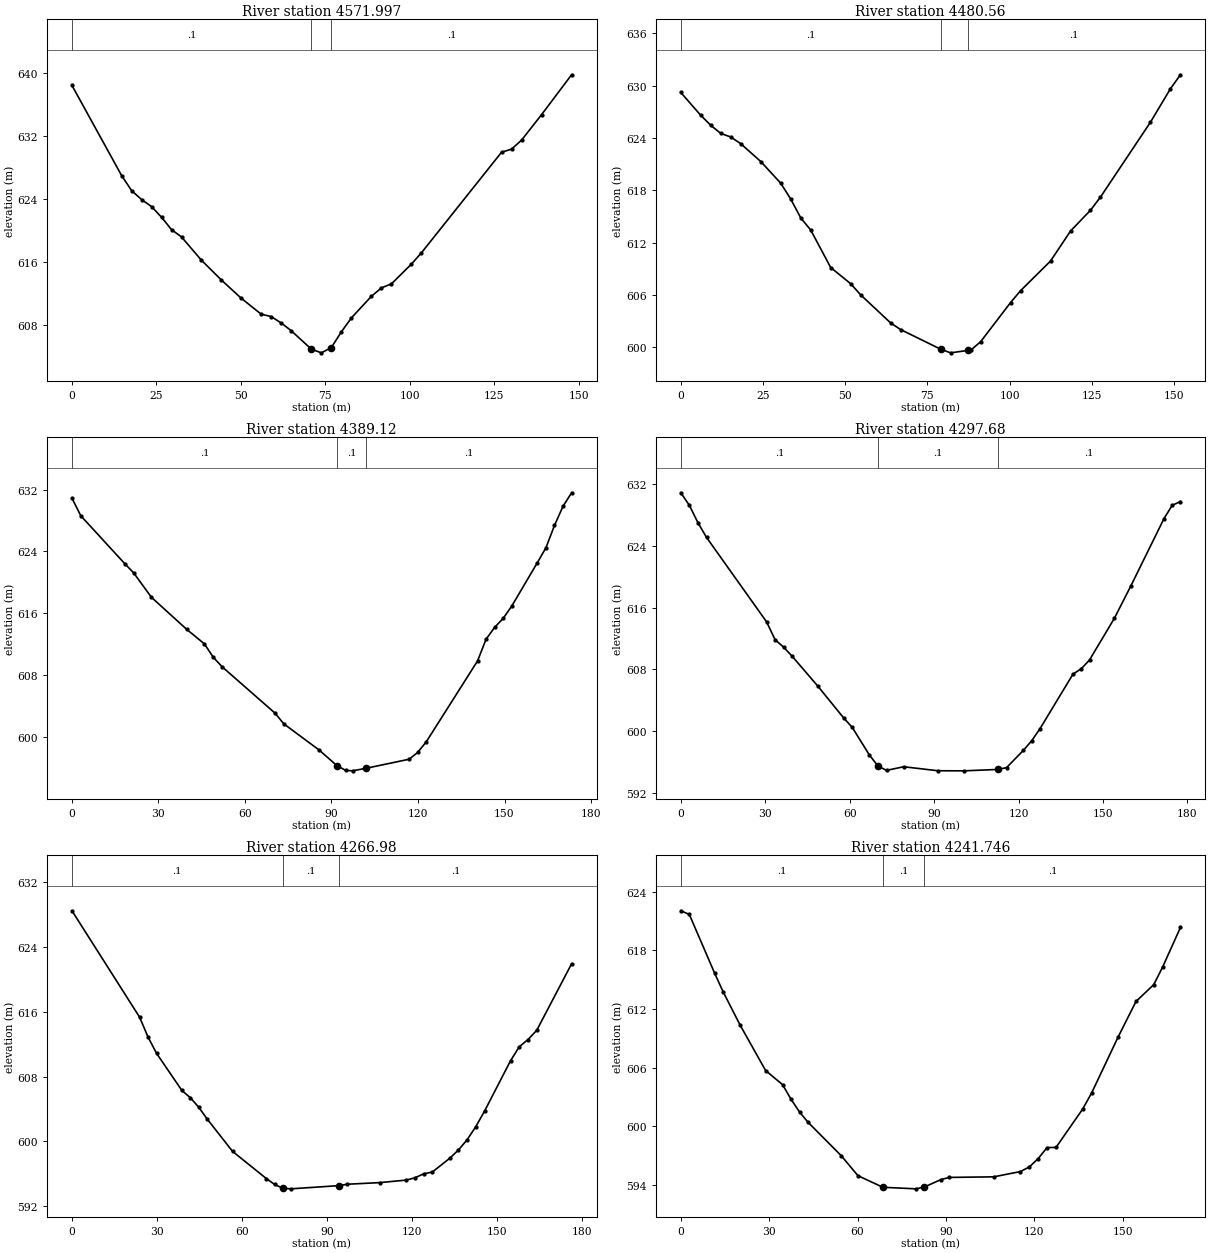
Type RM Length L Ch R = 1 ,4571.997,91.44,91.44,89.7
XS GIS Cut Line= 4
     619392.5673     4331481.482     619367.7754    4331541.4209
     619364.2297    4331546.2731     619332.3745    4331616.4198
#Sta/Elev= 30
       0  638.43   14.74  626.95   17.69  625.05   20.64  623.93   23.59  623.03
   26.54  621.68   29.48  620.11   32.43  619.19   38.33  616.23   44.23  613.72
   50.12   611.4   56.02  609.38   58.97  609.08   61.92  608.27   64.86   607.3
   70.87  604.94   73.84  604.47    76.8  605.14   79.76  607.14   82.73  608.91
   88.65  611.65   91.62  612.72   94.58  613.23   100.5  615.74  103.47  617.18
  127.17  629.94  130.14  630.34   133.1  631.48  139.03  634.72  147.91  639.78
#Mann= 3 , 0 , 0
       0      .1       0   70.87      .1       0    76.8      .1       0
Bank Sta=70.87,76.8
XS Rating Curve= 0 ,0
Exp/Cntr=0.3,0.1

Type RM Length L Ch R = 1 ,4480.56 ,87.92,91.44,94.63
XS GIS Cut Line= 2
     619322.3899    4331439.9107     619250.6749    4331573.9044
#Sta/Elev= 30
       0  629.23    6.08   626.6    9.12  625.46   12.16  624.53    15.2  624.12
   18.24  623.35   24.32  621.31    30.4  618.82   33.44     617   36.47  614.85
   39.51  613.45   45.59  609.15   51.67  607.29   54.71  606.01   63.83  602.79
   66.87  602.03   79.03  599.78   82.07  599.36   87.38  599.64   88.15  599.65
   91.19  600.63  100.31  605.13  103.35  606.49  112.46  609.89  118.54  613.33
  124.62  615.72  127.66  617.23  142.86  625.82  148.94  629.66  151.98  631.26
#Mann= 3 , 0 , 0
       0      .1       0   79.03      .1       0   87.38      .1       0
Bank Sta=79.03,87.38
XS Rating Curve= 0 ,0
Exp/Cntr=0.3,0.1

Type RM Length L Ch R = 1 ,4389.12 ,97.03,91.44,86.85
XS GIS Cut Line= 4
     619313.1921    4331410.0444     619226.0591    4331447.6657
     619219.2542    4331449.9989     619155.7647    4331482.1435
#Sta/Elev= 29
       0  630.89    3.06  628.61   18.37  622.39   21.43  621.21   27.55  618.07
    39.8  613.92   45.92  612.05   48.98  610.33   52.05  609.09   70.42  603.09
   73.48   601.7   85.72  598.32   91.85  596.31   94.91  595.69   97.31  595.63
   102.1  595.97  116.93  597.13  119.89  598.01  122.86  599.38  140.65  609.84
  143.61  612.65  146.58  614.18  149.54  615.34  152.51  616.93   161.4  622.55
  164.37  624.47  167.33  627.36   170.3  629.84  173.26  631.58
#Mann= 3 , 0 , 0
       0      .1       0   91.85      .1       0   102.1      .1       0
Bank Sta=91.85,102.1
XS Rating Curve= 0 ,0
Exp/Cntr=0.3,0.1

Type RM Length L Ch R = 1 ,4297.68 ,33.24,30.7,25.69
XS GIS Cut Line= 3
     619245.5984    4331322.1662      619151.337    4331394.4334
     619125.3376    4331447.0861
#Sta/Elev= 30
       0  630.86    3.05  629.23    6.09  626.98    9.14  625.08   30.46  614.16
    33.5  611.84   36.55  610.87   39.59  609.69   48.73  605.81   57.87  601.71
   60.91  600.49      67  596.92   70.05  595.49   73.09  594.93   79.18   595.4
   91.37  594.88   100.5  594.87  112.69  595.05  115.73  595.29  121.71  597.52
  124.65  598.76  127.58  600.31  139.33  607.39  142.26  608.08   145.2  609.22
  154.01   614.6  159.88   618.8  171.63   627.5  174.56  629.23   177.5  629.73
#Mann= 3 , 0 , 0
       0      .1       0   70.05      .1       0  112.69      .1       0
Bank Sta=70.05,112.69
XS Rating Curve= 0 ,0
Exp/Cntr=0.3,0.1

Type RM Length L Ch R = 1 ,4266.98 ,26.46,25.24,21.57
XS GIS Cut Line= 5
       619221.71    4331293.9859     619168.4625    4331337.3115
     619159.7841    4331355.3164      619144.941    4331368.8896
     619122.6127    4331432.7151
#Sta/Elev= 30
       0  628.49   23.88  615.35   26.86  612.89   29.85  610.89    38.8   606.3
   41.79   605.4   44.77  604.22   47.75  602.76   56.71  598.77   68.65  595.41
    71.5   594.7   74.36  594.23   77.21  594.15   94.38  594.55   97.25  594.72
  108.75  594.92  117.97  595.23  121.04  595.51  124.12     596  127.19  596.22
  133.34  597.92  136.41  598.94  139.48   600.2  142.56  601.83  145.63  603.74
  154.85  609.99  157.92   611.7     161  612.59  164.07  613.73  176.37  621.94
#Mann= 3 , 0 , 0
       0      .1       0   74.36      .1       0   94.38      .1       0
Bank Sta=74.36,94.38
XS Rating Curve= 0 ,0
Exp/Cntr=0.3,0.1

Type RM Length L Ch R = 1 ,4241.746,37.28,35.51,31.98
XS GIS Cut Line= 5
     619147.5365    4331263.6461     619146.7428    4331306.8261
      619142.774    4331326.1937     619137.3099    4331353.8647
     619118.2598    4331429.9854
#Sta/Elev= 30
       0  622.06    2.88  621.69   11.52  615.64    14.4  613.74   20.15  610.34
   28.79   605.7   34.55  604.25   37.43  602.75   40.31  601.45   43.19   600.4
   54.48  596.97   60.13  594.93    68.6  593.74   79.88  593.58    82.7  593.77
   88.34  594.53   91.16  594.75  106.25  594.81  115.31  595.35  118.32  595.82
  121.34  596.68  124.36  597.81  127.38  597.82  136.43  601.75  139.45  603.38
   148.5  609.15  154.54  612.77  160.58   614.5  163.59   616.3  169.63  620.35
#Mann= 3 , 0 , 0
       0      .1       0    68.6      .1       0    82.7      .1       0
Bank Sta=68.6,82.7
XS Rating Curve= 0 ,0
Exp/Cntr=0.3,0.1

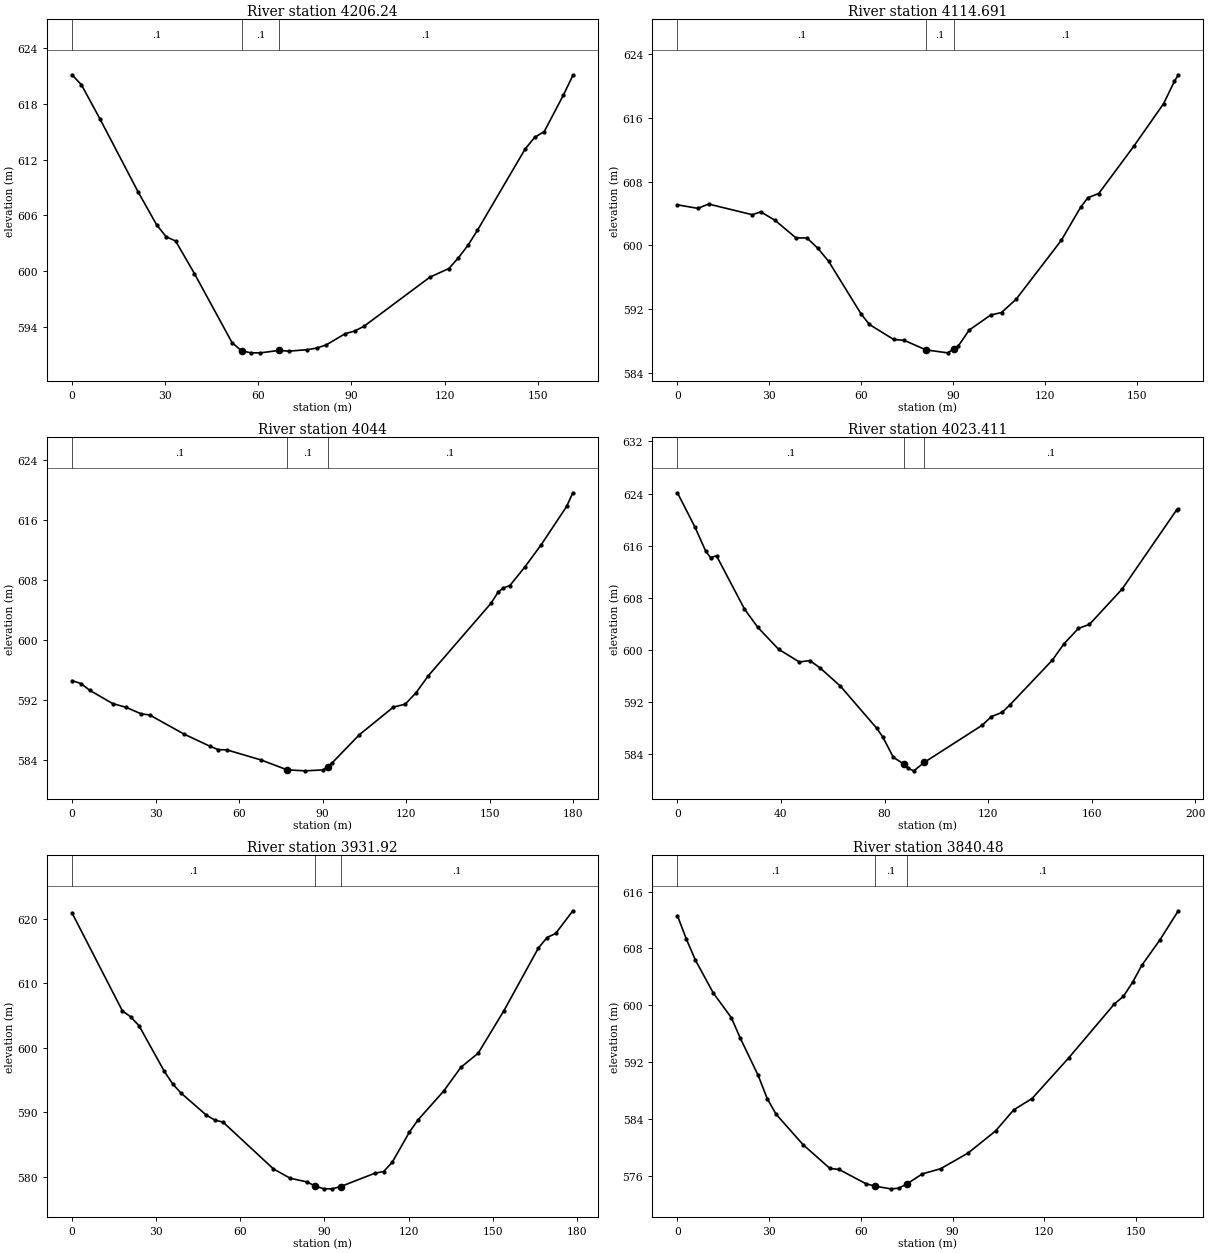
Type RM Length L Ch R = 1 ,4206.24 ,94.01,91.55,89.98
XS GIS Cut Line= 3
     619092.2578    4331270.8675     619115.0619    4331386.9628
     619112.1084    4331429.8881
#Sta/Elev= 30
       0  621.16    3.03  620.08     9.1  616.34   21.24  608.56    27.3  604.96
   30.34  603.69   33.37  603.24   39.44  599.72   51.57  592.27   54.61   591.4
   57.64  591.18   60.67  591.18   66.74  591.44   69.77  591.36   75.84  591.52
   78.88   591.7   81.91  592.04   87.98  593.24   91.01  593.53   94.04  594.04
  115.28  599.34  121.39  600.27  124.46  601.42  127.53  602.77  130.61   604.4
  145.97  613.16  149.05  614.42  152.12  615.04  158.27  618.96  161.34   621.1
#Mann= 3 , 0 , 0
       0      .1       0   54.61      .1       0   66.74      .1       0
Bank Sta=54.61,66.74
XS Rating Curve= 0 ,0
Exp/Cntr=0.3,0.1

Type RM Length L Ch R = 1 ,4114.691,70.8,70.8,70.8
XS GIS Cut Line= 3
618983.890750047  4331309.467047     619008.6401    4331351.6216
     619064.8802     4331451.584
#Sta/Elev= 30
       0 605.079   6.634 604.642  10.199 605.178  24.459 603.839  27.212 604.198
  31.901 603.131  38.719 600.929  42.284 600.924  45.849 599.632  49.408 597.977
   59.99 591.379  62.697 590.069  70.573 588.194    74.1 588.071  81.155 586.877
   88.21 586.507  90.311 586.993  91.737 587.376  95.265  589.36  102.32 591.256
 105.847 591.568 110.627 593.242 125.394 600.642 131.664 604.768 134.066 605.981
 137.594 606.504 149.003 612.414 158.758  617.77 162.286 620.568  163.58 621.404
#Mann= 3 , 0 , 0
       0      .1       0  81.155      .1       0  90.311      .1       0
Bank Sta=81.155,90.311
XS Rating Curve= 0 ,0
Exp/Cntr=0.3,0.1

Type RM Length L Ch R = 1 ,4044    ,20.4,20.4,20.4
XS GIS Cut Line= 4
618955.2142330194331324.23989432618959.5340035174331399.83587804
618968.7135158254331426.83444365619020.0107904874331482.45148881
#Sta/Elev= 30
       0 594.559   3.251 594.169    6.33 593.278  14.612   591.5  19.333 591.015
  24.806 590.138  27.885 589.981  40.202 587.437   49.44 585.827  52.519 585.357
  55.598 585.327  67.916 583.977  77.276 582.662  83.726  582.53   90.22 582.654
  91.815 583.106  93.467 583.606 103.209 587.348 115.459 591.042 119.642 591.412
 123.543 592.935 128.006 595.228 150.444 604.859   153.1 606.388 154.979 606.922
 157.282 607.251 162.704 609.747 168.582 612.719 177.651 617.794 179.897 619.619
#Mann= 3 , 0 , 0
       0      .1       0  77.276      .1       0  91.815      .1       0
Bank Sta=77.276,91.815
XS Rating Curve= 0 ,0
Exp/Cntr(USF)=0,0
Exp/Cntr=0.3,0.1

Type RM Length L Ch R = 1 ,4023.411,84.86,91.49,94.99
XS GIS Cut Line= 3
618885.7638598764331346.86426925     618940.4786    4331411.4676
     619014.8738    4331490.9012
#Sta/Elev= 30
       0 624.132   6.834  618.81  10.863  615.22  12.802 614.169  15.091 614.457
  25.889 606.299  31.006   603.5  39.064 600.127  47.121 598.164   51.15 598.394
  55.179 597.231  62.971 594.457  76.929  588.03  79.351 586.648  83.379 583.557
  87.533 582.489  89.134 581.833  91.309 581.469   95.34 582.762 117.827 588.493
  121.23 589.782 125.442 590.444 128.284 591.525 144.811 598.445 149.308 600.955
 154.926 603.332 159.138 603.927 171.795 609.365 192.834 621.497 193.492 621.623
#Mann= 3 , 0 , 0
       0      .1       0  87.533      .1       0   95.34      .1       0
Bank Sta=87.533,95.34
XS Rating Curve= 0 ,0
Exp/Cntr=0.3,0.1

Type RM Length L Ch R = 1 ,3931.92 ,95.7,91.44,91.88
XS GIS Cut Line= 3
     618846.3374    4331342.6062     618858.6284    4331437.5511
     618875.1736    4331518.6825
#Sta/Elev= 30
       0  620.94   17.95  605.75   20.94  604.81   23.93  603.41   32.91  596.36
    35.9   594.4   38.89  592.98   47.87  589.58   50.86  588.82   53.85  588.48
    71.8  581.23   77.79  579.78   83.77  579.21   86.76  578.56   89.75  578.15
   92.75  578.14   95.74  578.49     108  580.57  111.07  580.82  114.14  582.26
  120.27  586.94  123.34  588.83  132.54  593.34  138.67  597.01   144.8  599.19
     154   605.8  166.27  615.51  169.34  617.12   172.4  617.75  178.54  621.27
#Mann= 3 , 0 , 0
       0      .1       0   86.76      .1       0   95.74      .1       0
Bank Sta=86.76,95.74
XS Rating Curve= 0 ,0
Exp/Cntr=0.3,0.1

Type RM Length L Ch R = 1 ,3840.48 ,95.56,91.44,87.03
XS GIS Cut Line= 4
     618724.3607    4331398.0322     618767.7245    4331445.8702
     618770.0185    4331461.2685     618798.1796    4331540.1138
#Sta/Elev= 30
       0  612.62    2.93   609.3    5.87  606.36   11.74  601.71   17.61  598.26
   20.54  595.37   26.41  590.11   29.35  586.85   32.28  584.63   41.09  580.35
   49.89  576.99   52.83  576.86   61.63  574.85   64.57   574.5   69.76  574.12
   72.35   574.2   74.95  574.78   80.14  576.23   86.12  576.96   95.09  579.17
  104.06  582.27  110.04  585.26  116.02  586.85  127.98  592.56  142.93  600.17
  145.92  601.26  148.91  603.23   151.9  605.61  157.88  609.23  163.86  613.31
#Mann= 3 , 0 , 0
       0      .1       0   64.57      .1       0   74.95      .1       0
Bank Sta=64.57,74.95
XS Rating Curve= 0 ,0
Exp/Cntr=0.3,0.1

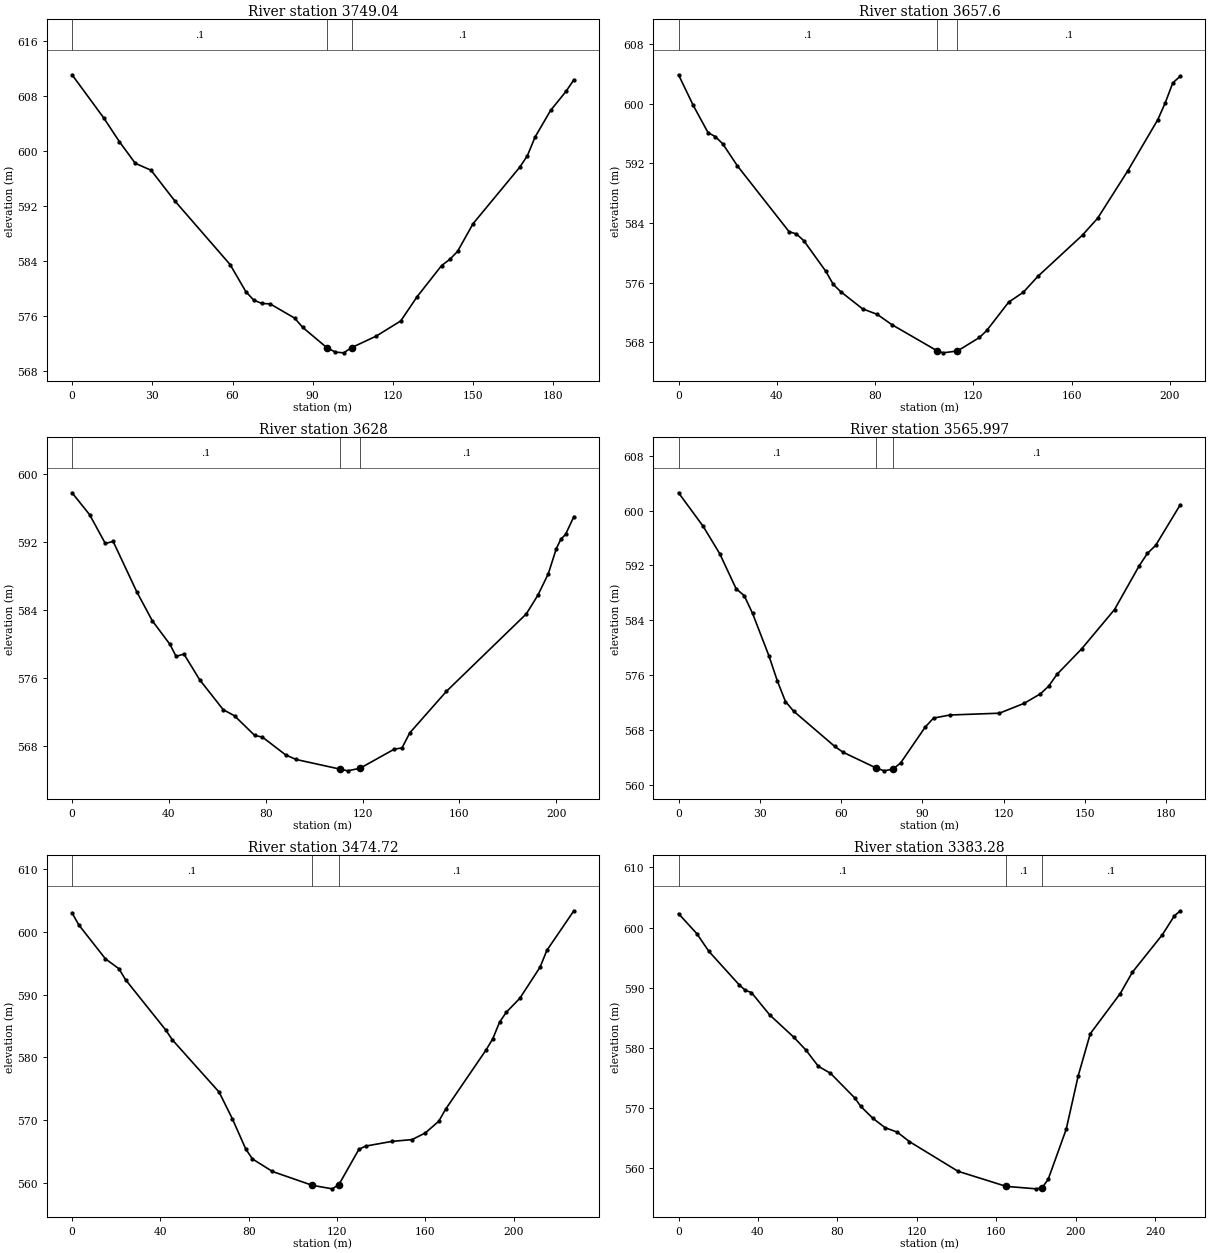
Type RM Length L Ch R = 1 ,3749.04 ,81.86,91.44,101.07
XS GIS Cut Line= 4
     618624.1099    4331463.9136     618678.4987    4331504.6496
     618748.5037    4331526.3755     618782.8602    4331557.5763
#Sta/Elev= 30
       0  611.15   11.82  604.88   17.73  601.39   23.64  598.26   29.54  597.25
   38.41  592.79   59.09  583.52      65  579.57   67.95  578.33   71.01  577.85
   74.06  577.79   83.22  575.72   86.28  574.36   95.44  571.36   98.49  570.77
  101.55  570.66   104.6  571.43  113.76   573.1  122.93  575.31  129.03  578.83
   138.2  583.37  141.25  584.27  144.15  585.42  149.95  589.46  167.36  597.66
  170.26  599.35  173.16  602.09  178.96  605.96  184.76  608.75  187.66  610.42
#Mann= 3 , 0 , 0
       0      .1       0   95.44      .1       0   104.6      .1       0
Bank Sta=95.44,104.6
XS Rating Curve= 0 ,0
Exp/Cntr=0.3,0.1

Type RM Length L Ch R = 1 ,3657.6  ,29.3,29.3,29.3
XS GIS Cut Line= 4
     618599.5036    4331473.4386      618634.716    4331529.2432
     618650.4932    4331614.0451       618681.26    4331656.0015
#Sta/Elev= 30
       0  603.91       6  599.79      12  596.15      15   595.6      18  594.64
   23.99  591.67   44.99  582.85   47.99  582.54   50.99  581.64   59.99  577.51
   62.99  575.77   65.99   574.8   74.91  572.49   80.86  571.75   86.81  570.37
  105.07  566.89  107.63  566.58  113.55  566.83   122.5  568.64  125.47  569.58
   134.4  573.39  140.34  574.71  146.29  576.85  164.48   582.4  170.61  584.65
  182.85     591  195.09  597.88  198.15  600.16  201.21  602.83  204.27  603.72
#Mann= 3 , 0 , 0
       0      .1       0  105.07      .1       0  113.55      .1       0
Bank Sta=105.07,113.55
XS Rating Curve= 0 ,0
Exp/Cntr=0.3,0.1

Type RM Length L Ch R = 1 ,3628    ,62.3,62.3,62.3
XS GIS Cut Line= 4
618580.4741423284331474.35191912618604.7728513794331545.62813234
618623.6718473074331610.42468981618662.0098104764331662.26193578
#Sta/Elev= 30
       0 597.814   7.234 595.242   13.73 591.849  16.978 592.084  26.722 586.163
  33.129 582.759  40.462 579.964  42.962 578.558   46.21 578.837  52.706 575.808
   62.45 572.286  67.107 571.568   75.44 569.255  78.642 569.062  88.249  566.96
  92.579 566.426 110.666 565.294 113.868 565.091 118.978 565.399 133.083 567.639
 136.285 567.787 139.487 569.554 154.651 574.453 187.622 583.557 192.376 585.741
 196.703 588.271 200.024 591.241 201.873 592.328 203.847 592.922 207.275 595.003
#Mann= 3 , 0 , 0
       0      .1       0 110.666      .1       0 118.978      .1       0
Bank Sta=110.666,118.978
XS Rating Curve= 0 ,0
Exp/Cntr(USF)=0,0
Exp/Cntr=0.3,0.1

Type RM Length L Ch R = 1 ,3565.997,97.8,91.28,88.83
XS GIS Cut Line= 2
     618517.7472    4331567.8951     618647.9225    4331699.6579
#Sta/Elev= 30
       0  602.59    9.11  597.69   15.18  593.73   21.25  588.61   24.29  587.57
   27.33     585    33.4  578.79   36.44   575.2   39.47  572.16   42.51  570.75
   57.69  565.61   60.73  564.77   72.87  562.49   75.91  562.06   79.22  562.33
   81.98  563.21   91.09  568.46   94.13  569.75   100.2   570.2  118.42  570.46
  127.53  571.89   133.6  573.29  136.64  574.41  139.68  576.12  148.78  579.83
  160.93  585.57  170.04  591.95  173.08  593.76  176.11  594.92  185.22  600.86
#Mann= 3 , 0 , 0
       0      .1       0   72.87      .1       0   79.22      .1       0
Bank Sta=72.87,79.22
XS Rating Curve= 0 ,0
Exp/Cntr=0.3,0.1

Type RM Length L Ch R = 1 ,3474.72 ,88.36,91.44,93.53
XS GIS Cut Line= 4
     618413.7658    4331648.8577     618482.2716    4331687.5727
     618564.0747    4331708.0235     618620.1412    4331739.3454
#Sta/Elev= 30
       0  603.05    3.03  601.14   15.13  595.71   21.19  594.15   24.21  592.39
   42.37  584.38    45.4  582.79   66.58  574.45   72.64  570.14   78.69  565.33
    81.7  563.77   90.73  561.77   108.8  559.56  117.84     559  120.85  559.69
  129.88   565.3  132.89  565.82  144.94  566.58  153.97  566.86     160  567.93
  166.07   569.8  169.13   571.7  187.47  581.17  190.53  582.97  193.59  585.61
  196.65   587.2  202.77  589.42  211.94   594.4     215  597.07  227.23  603.39
#Mann= 3 , 0 , 0
       0      .1       0   108.8      .1       0  120.85      .1       0
Bank Sta=108.8,120.85
XS Rating Curve= 0 ,0
Exp/Cntr=0.3,0.1

Type RM Length L Ch R = 1 ,3383.28 ,81.39,91.47,91.37
XS GIS Cut Line= 4
     618362.2513    4331669.7334     618458.1647    4331768.5017
     618492.1599    4331781.4386     618560.3074    4331820.6235
#Sta/Elev= 30
       0  602.31    9.18     599    15.3  596.04   30.59  590.47   33.65  589.57
   36.71   589.2   45.89  585.49   58.13  581.75   64.25   579.6   70.37  576.95
   76.49  575.79   88.72  571.69   91.78  570.27    97.9  568.29  104.02  566.74
  110.14     566  116.26  564.43  140.71   559.5  164.96  556.99   180.1  556.58
  183.12  556.77  186.14  558.18  195.21  566.49  201.26  575.39  207.31  582.36
  222.42  589.04  228.47  592.56  243.59   598.8  249.64  601.94  252.66  602.79
#Mann= 3 , 0 , 0
       0      .1       0  164.96      .1       0  183.12      .1       0
Bank Sta=164.96,183.12
XS Rating Curve= 0 ,0
Exp/Cntr=0.3,0.1