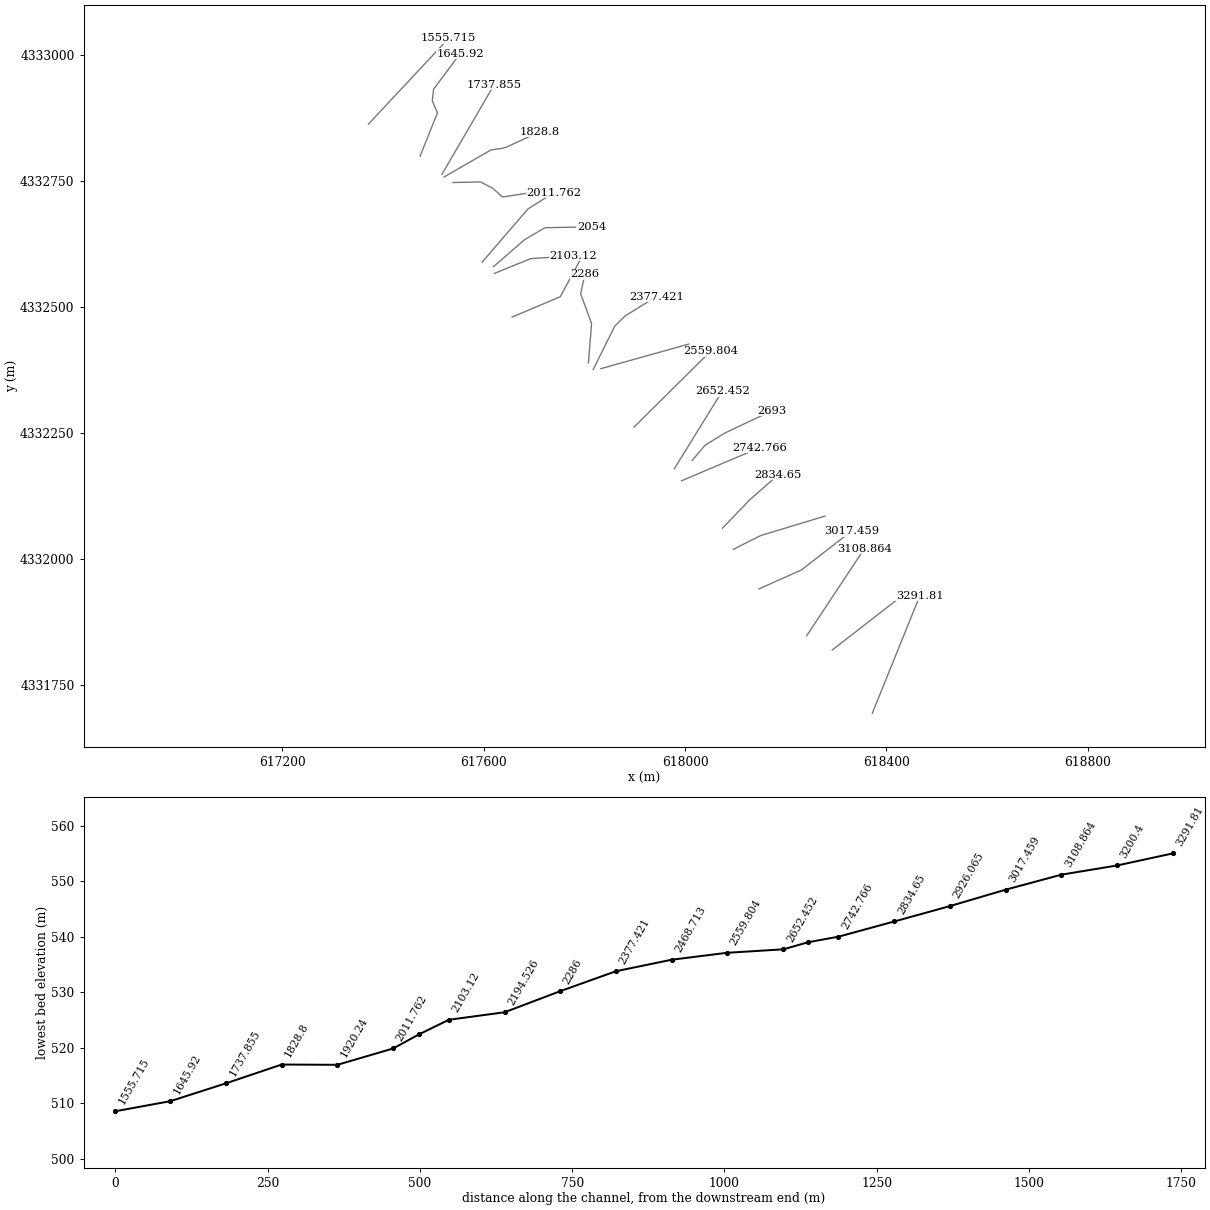
HEC-RAS study MillRun.prj: MillRun

--- MillRun.g01 (geometry) --- (continued)

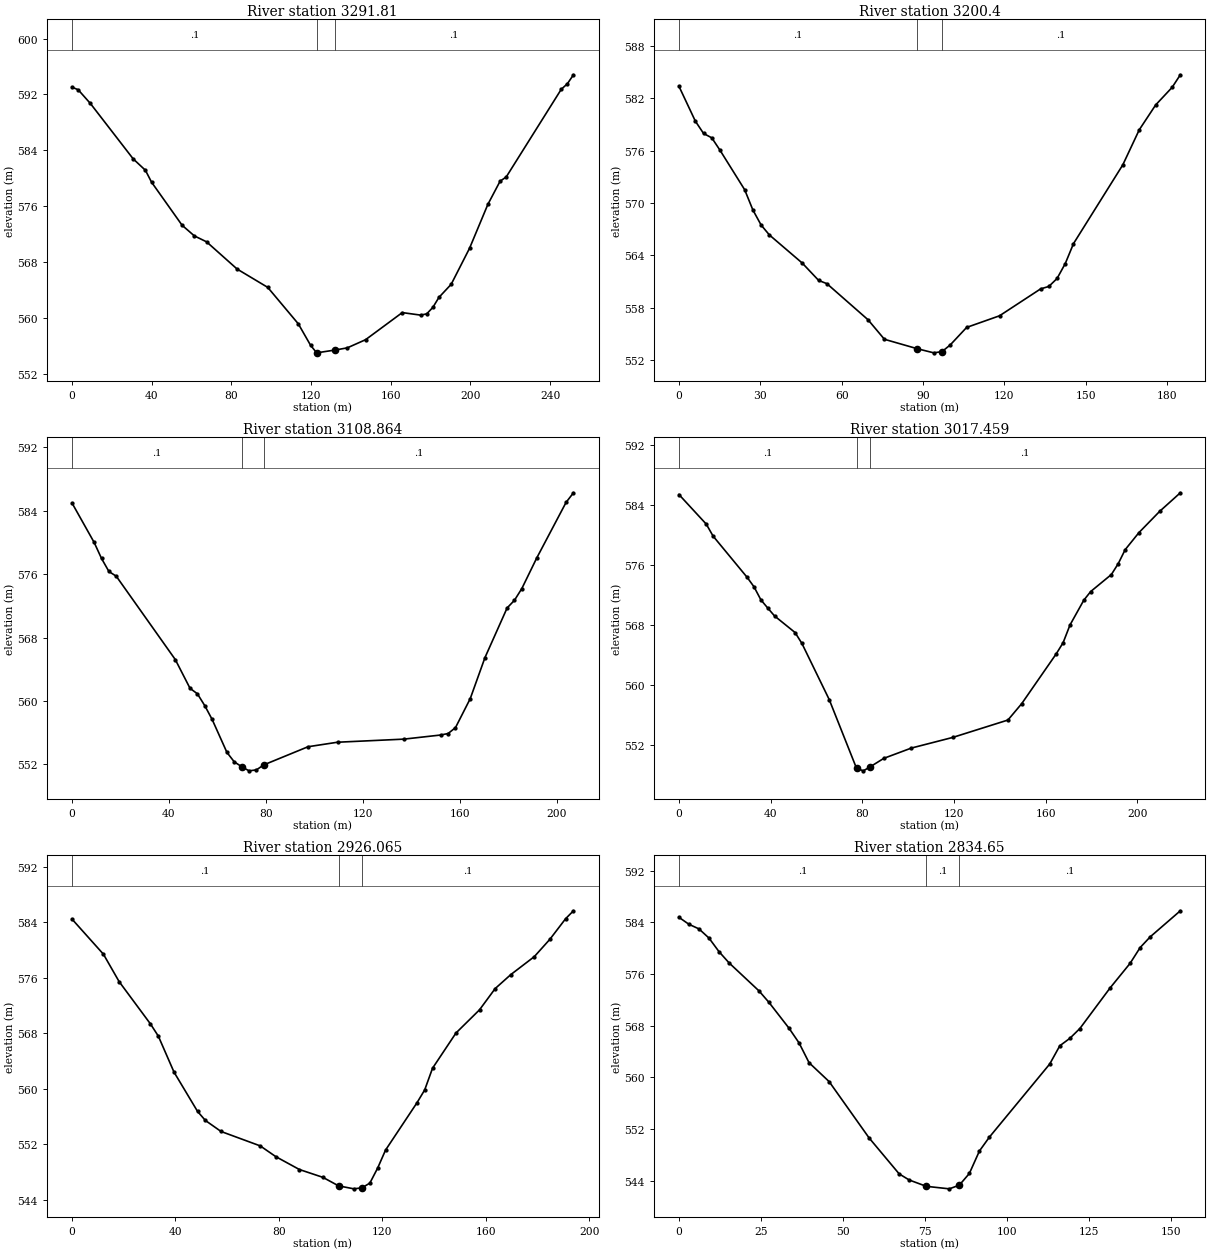
Type RM Length L Ch R = 1 ,3291.81 ,99.37,91.41,78.36
XS GIS Cut Line= 2
     618371.7763     4331693.546     618466.2327    4331926.9089
#Sta/Elev= 30
       0  593.04    3.07  592.68    9.21  590.71    30.7  582.78   36.84  581.15
   39.91  579.45   55.26  573.28    61.4  571.76   67.54  570.91   82.89  567.01
   98.25  564.39   113.6  559.17  119.74  556.11  122.81  555.02  132.02  555.42
  138.16  555.73  147.37   556.9  165.79  560.78     175  560.42  178.07   560.6
  181.14  561.52  184.21  562.96  190.35  564.83  199.56  569.98  208.77  576.27
  214.91  579.59  217.98  580.19  245.61  592.74  248.68  593.53  251.75  594.82
#Mann= 3 , 0 , 0
       0      .1       0  122.81      .1       0  132.02      .1       0
Bank Sta=122.81,132.02
XS Rating Curve= 0 ,0
Exp/Cntr=0.3,0.1

Type RM Length L Ch R = 1 ,3200.4  ,89.66,91.54,94.84
XS GIS Cut Line= 2
     618292.2839    4331819.2282      618438.351    4331932.5042
#Sta/Elev= 30
       0  583.37    6.06  579.37    9.09  577.96   12.12  577.46   15.15  576.04
   24.24  571.52   27.27   569.2    30.3  567.48   33.33  566.35   45.45  563.13
   51.51  561.14   54.54  560.77    69.7  556.64   75.76   554.4   87.88  553.32
   93.94  552.85   96.97  552.99     100  553.75  106.06  555.76  118.18  557.09
  133.33  560.17  136.36  560.45  139.39  561.36  142.42  563.07  145.45  565.35
  163.63  574.37  169.69  578.38  175.75  581.23  181.81  583.24  184.84  584.68
#Mann= 3 , 0 , 0
       0      .1       0   87.88      .1       0   96.97      .1       0
Bank Sta=87.88,96.97
XS Rating Curve= 0 ,0
Exp/Cntr=0.3,0.1

Type RM Length L Ch R = 1 ,3108.864,94.02,91.4,79.73
XS GIS Cut Line= 2
      618241.601    4331847.5338     618355.9435    4332020.0494
#Sta/Elev= 30
       0  584.97    9.13     580   12.17  577.98   15.22  576.34   18.26  575.74
   42.61  565.23    48.7   561.6   51.74  560.91   54.79  559.41   57.83  557.67
   63.92  553.52   66.96  552.32      70  551.72   73.05  551.19   76.09  551.31
   79.13  551.94    97.4  554.23  109.57   554.8  136.96  555.19  152.18  555.71
  155.23   555.9  158.27  556.64  164.36   560.3  170.44  565.48  179.58  571.74
  182.62  572.71  185.66  574.19  191.75  578.01  203.92  585.06  206.97  586.27
#Mann= 3 , 0 , 0
       0      .1       0      70      .1       0   79.13      .1       0
Bank Sta=70,79.13
XS Rating Curve= 0 ,0
Exp/Cntr=0.3,0.1

Type RM Length L Ch R = 1 ,3017.459,91.99,91.39,87.16
XS GIS Cut Line= 3
     618146.7477    4331940.3366     618231.0824    4331977.9855
     618330.8981    4332055.4305
#Sta/Elev= 30
       0  585.37   11.92  581.42    14.9  579.82   29.79   574.3   32.77  573.04
   35.75  571.31   38.73  570.22   41.71  569.16   50.65  566.95   53.63   565.5
   65.54  558.01   77.46  548.83   80.44  548.49   83.42  549.03   89.38  550.16
  101.38  551.53  119.43  552.95  143.49  555.27  149.51  557.46  164.55   564.1
  167.56  565.59  170.57  567.96  176.58  571.26  179.59  572.42  188.61  574.69
  191.62  576.15  194.63  578.01  200.65  580.29  209.67  583.12  218.69   585.6
#Mann= 3 , 0 , 0
       0      .1       0   77.46      .1       0   83.42      .1       0
Bank Sta=77.46,83.42
XS Rating Curve= 0 ,0
Exp/Cntr=0.3,0.1

Type RM Length L Ch R = 1 ,2926.065,89.17,91.41,93.33
XS GIS Cut Line= 3
     618095.9476     4332018.918     618150.1475    4332046.1984
     618277.7167    4332084.7993
#Sta/Elev= 30
       0  584.47   12.14  579.41    18.2  575.46   30.34  569.34   33.37  567.59
   39.44  562.39   48.54  556.72   51.58  555.41   57.64  553.82   72.79  551.74
   78.85  550.18   87.94  548.33   97.03   547.2  103.09  545.97  109.03  545.54
  112.17  545.69   115.2  546.37  118.23  548.55  121.26  551.13  133.38  557.94
  136.41  559.82  139.44  562.95  148.52  568.04  157.61  571.38  163.67  574.45
  169.73  576.47  178.81  579.06  184.87  581.58  190.93  584.54  193.96  585.68
#Mann= 3 , 0 , 0
       0      .1       0  103.09      .1       0  112.17      .1       0
Bank Sta=103.09,112.17
XS Rating Curve= 0 ,0
Exp/Cntr=0.3,0.1

Type RM Length L Ch R = 1 ,2834.65 ,93.74,91.88,90.96
XS GIS Cut Line= 3
     618074.5163    4332060.9868     618129.5176    4332118.1781
     618184.8478    4332166.5558
#Sta/Elev= 30
       0  584.79    3.05  583.71     6.1     583    9.16  581.58   12.21  579.48
   15.26  577.75   24.41   573.4   27.47  571.61   33.57  567.62   36.62  565.35
   39.67  562.29   45.78  559.37   57.98  550.64   67.14  545.08   70.19  544.14
    75.4  543.16   82.41  542.77   85.47  543.34   88.53  545.15    91.6  548.63
   94.66  550.79  113.03  562.09   116.1  564.91  119.16  566.06  122.22  567.58
  131.41  573.85  137.53  577.67  140.59  580.11  143.66  581.77  152.84   585.8
#Mann= 3 , 0 , 0
       0      .1       0    75.4      .1       0   85.47      .1       0
Bank Sta=75.4,85.47
XS Rating Curve= 0 ,0
Exp/Cntr=0.3,0.1

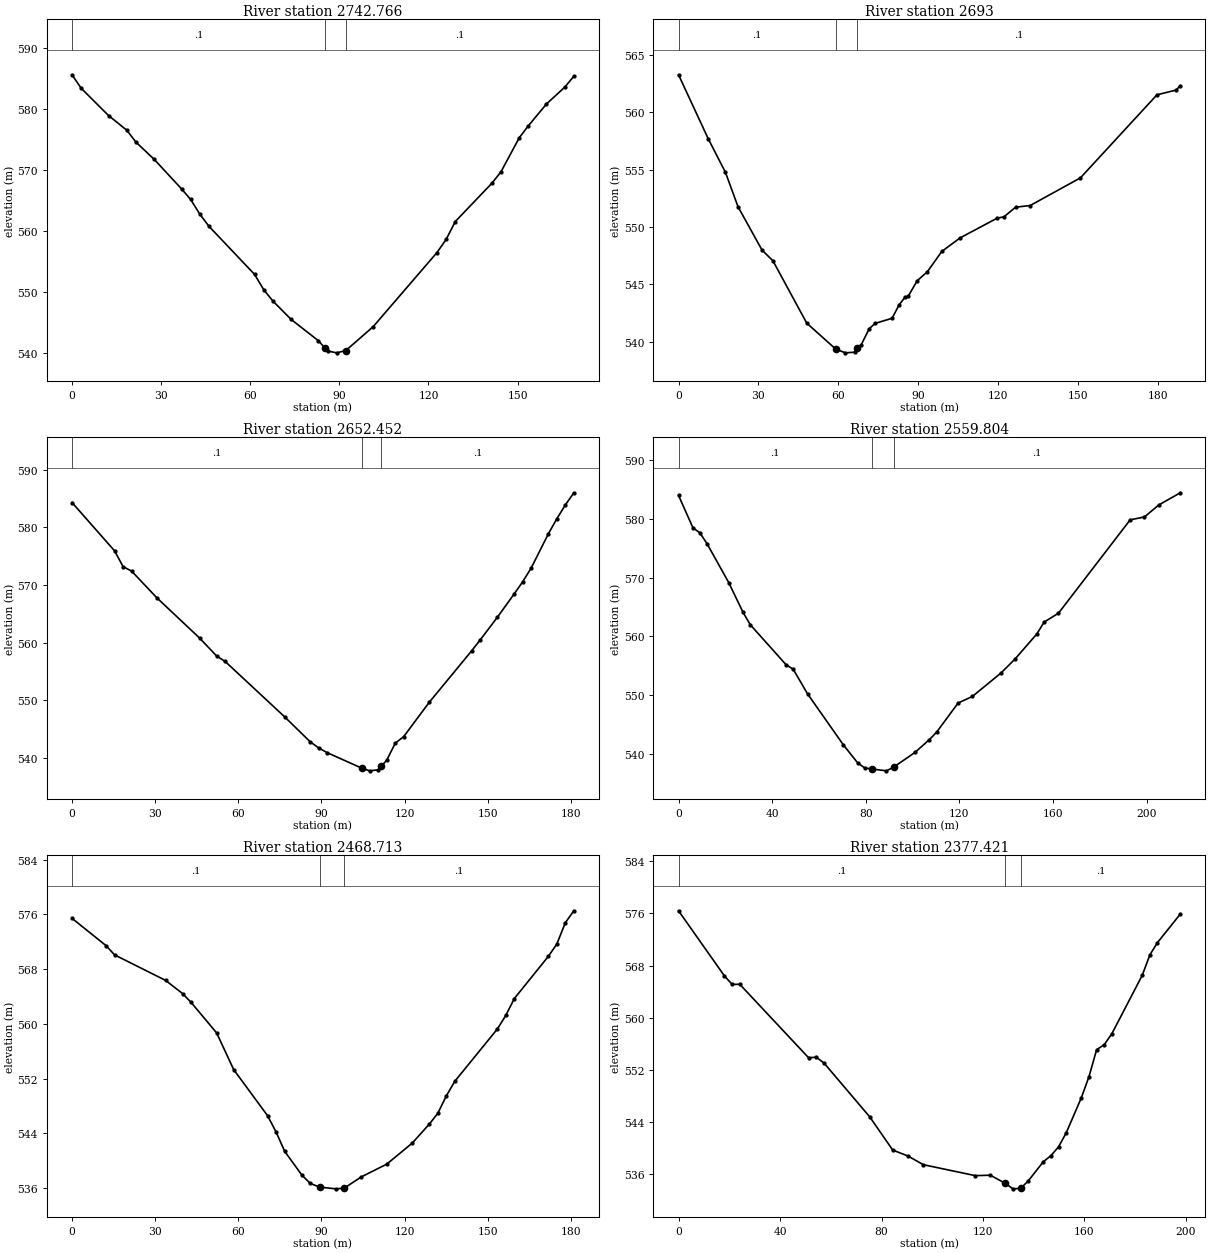
Type RM Length L Ch R = 1 ,2742.766,49.8,49.8,49.8
XS GIS Cut Line= 2
      617992.998    4332154.8876     618148.5733     4332220.769
#Sta/Elev= 30
       0  585.56    3.07  583.35   12.29  578.88   18.43  576.48    21.5  574.53
   27.65  571.71   36.86  566.87   39.93  565.14   43.01  562.73   46.08  560.75
   61.44  552.87   64.51  550.38   67.58  548.52   73.72  545.51   82.94     542
   85.11  540.82   86.01  540.33   89.08  540.02   92.15  540.39  101.37   544.3
  122.87  556.45  125.94  558.59  129.02  561.52   141.3  567.77  144.38  569.64
  150.52  575.21  153.59  577.18  159.73  580.78  165.88  583.53  168.95  585.32
#Mann= 3 , 0 , 0
       0      .1       0   85.11      .1       0   92.15      .1       0
Bank Sta=85.11,92.15
XS Rating Curve= 0 ,0
Exp/Cntr=0.3,0.1

Type RM Length L Ch R = 1 ,2693    ,40.5,40.5,40.5
XS GIS Cut Line= 4
618014.0442357954332195.21362096618039.9628587824332225.45201444
618078.3008219514332249.21075218618171.7158589674332293.48839979
#Sta/Elev= 30
       0  563.28  11.115 557.714    17.6 554.772  22.324 551.768   31.36 547.976
  35.409 547.059  48.127 541.609  58.977 539.354  62.594 539.024   66.21  539.08
  67.077 539.404  68.476 539.689  71.543 541.123  73.776 541.592  80.148  542.04
  82.708 543.182  84.929  543.86  86.227  543.98  89.557 545.313  93.404 546.104
   98.79  547.87 105.714 549.058 119.563 550.771 122.115 550.887 126.487 551.729
 131.962 551.875 150.826 554.289 179.536 561.531 186.714 561.947 188.307 562.329
#Mann= 3 , 0 , 0
       0      .1       0  58.977      .1       0  67.077      .1       0
Bank Sta=58.977,67.077
XS Rating Curve= 0 ,0
Exp/Cntr(USF)=0,0
Exp/Cntr=0.3,0.1

Type RM Length L Ch R = 1 ,2652.452,93.6,92.65,90.67
XS GIS Cut Line= 2
     617978.7105    4332178.7002     618073.9607     4332332.688
#Sta/Elev= 30
       0  584.27   15.34   575.9   18.41  573.16   21.48  572.39   30.69  567.71
   46.03  560.77   52.17  557.66   55.24  556.72   76.72  547.11   85.93  542.78
      89  541.72   92.07   540.9   104.7  538.18  107.41  537.75  110.48  537.93
  111.65  538.57  113.55  539.61  116.62  542.54  119.69   543.7  128.89  549.64
  144.24  558.59  147.31  560.48  153.45  564.37  159.58  568.46  162.65  570.57
  165.72  572.97  171.86  578.84  174.93  581.47     178  583.86  181.07  585.97
#Mann= 3 , 0 , 0
       0      .1       0   104.7      .1       0  111.65      .1       0
Bank Sta=104.7,111.65
XS Rating Curve= 0 ,0
Exp/Cntr=0.3,0.1

Type RM Length L Ch R = 1 ,2559.804,93.39,91.09,86.73
XS GIS Cut Line= 2
     617898.5416    4332261.2503     618050.9419    4332412.0631
#Sta/Elev= 30
       0  584.01    6.13  578.51    9.19   577.6   12.25  575.73   21.44  569.17
   27.57  564.09   30.63     562   45.94  555.19   49.01  554.41   55.13  550.22
   70.45  541.53   76.57  538.46   79.64   537.6    82.7  537.43   88.83  537.12
   91.89  537.74  101.08  540.27   107.2  542.44  110.27   543.7  119.46  548.66
  125.58  549.79  137.83  553.79  143.96  556.23  153.15  560.45  156.21  562.44
  162.34  563.95  192.97  579.84  199.09  580.34  205.22  582.38  214.41  584.45
#Mann= 3 , 0 , 0
       0      .1       0    82.7      .1       0   91.89      .1       0
Bank Sta=82.7,91.89
XS Rating Curve= 0 ,0
Exp/Cntr=0.3,0.1

Type RM Length L Ch R = 1 ,2468.713,89.4,91.29,92.69
XS GIS Cut Line= 2
      617832.766    4332377.2439     618007.1576    4332426.0144
#Sta/Elev= 30
       0  575.41   12.28  571.42   15.35  570.07   33.76  566.34    39.9  564.41
   42.97  563.12   52.18  558.66   58.31  553.31   70.59  546.54   73.66  544.15
   76.73  541.35   82.87  537.91   85.94  536.66   89.31  536.13   95.15  535.87
   98.21  535.97  104.35  537.61  113.56  539.48  122.77  542.56  128.91  545.33
  131.98  546.91  135.04  549.44  138.11  551.59  153.46  559.23  156.53  561.23
   159.6  563.69  171.88  569.86  174.94  571.66  178.01  574.78  181.08  576.52
#Mann= 3 , 0 , 0
       0      .1       0   89.31      .1       0   98.21      .1       0
Bank Sta=89.31,98.21
XS Rating Curve= 0 ,0
Exp/Cntr=0.3,0.1

Type RM Length L Ch R = 1 ,2377.421,72.98,91.42,102.24
XS GIS Cut Line= 4
     617817.6848    4332375.6564     617860.7398    4332462.0024
     617881.7921    4332482.3931     617943.0975    4332520.1192
#Sta/Elev= 30
       0  576.41   18.09  566.43   21.11  565.13   24.12  565.15   51.26  553.89
   54.27  553.97   57.29   553.1   75.38  544.82   84.42  539.74   90.45  538.83
   96.49   537.5     117  535.82  122.86  535.89  128.79  534.65  131.79   533.8
  134.83  533.87  137.79  534.99  143.79  537.96  146.79  538.89  149.79  540.24
  152.79  542.37  158.79  547.78  161.79  551.01  164.78  555.12  167.78  555.89
  170.78  557.56  182.78  566.53  185.78  569.66  188.78  571.54  197.78  575.91
#Mann= 3 , 0 , 0
       0      .1       0  128.79      .1       0  134.83      .1       0
Bank Sta=128.79,134.83
XS Rating Curve= 0 ,0
Exp/Cntr=0.3,0.1

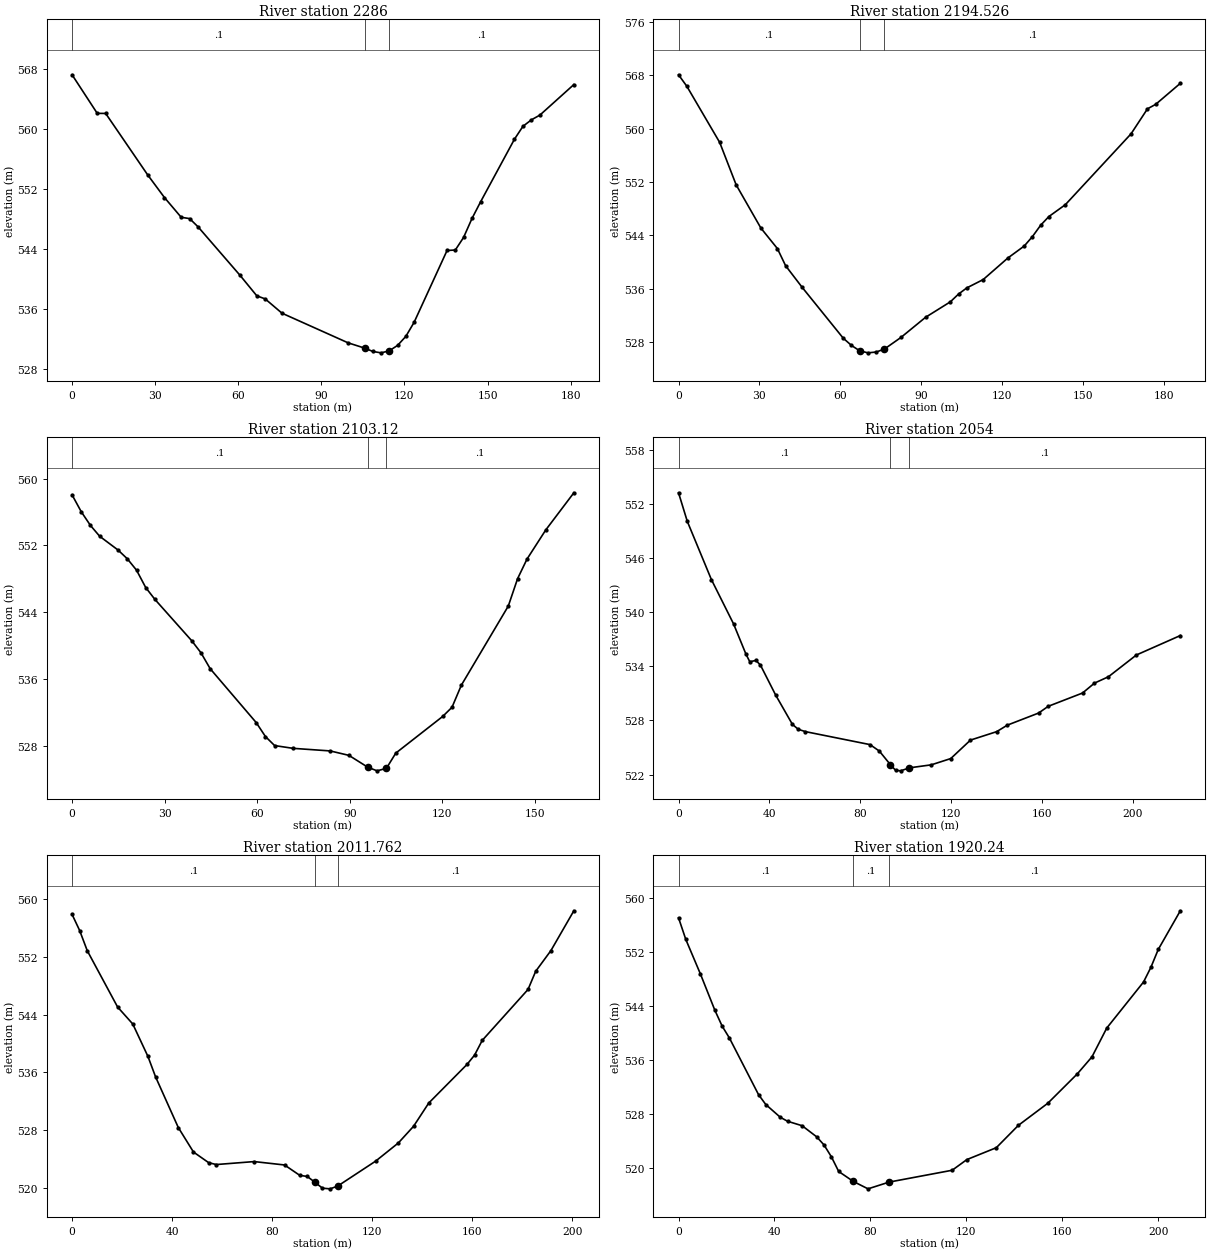
Type RM Length L Ch R = 1 ,2286    ,102.94,91.47,81.3
XS GIS Cut Line= 4
     617808.1598    4332388.3564     617814.4771    4332466.9258
     617792.8619    4332525.5956      617801.016    4332564.5693
#Sta/Elev= 30
       0  567.18    9.09  562.05   12.13  562.04   27.28  553.88   33.35  550.86
   39.41  548.23   42.44  548.06   45.47  546.97   60.63  540.52    66.7  537.79
   69.73  537.38   75.79  535.48   99.66  531.54  105.62  530.84   108.6  530.39
  111.57  530.21  114.48  530.47  117.53   531.2  120.51   532.4  123.48  534.26
  135.39  543.82  138.37  543.88  141.35  545.55  144.41  548.09  147.47  550.27
  159.73  558.62  162.79  560.33  165.85  561.19  168.91  561.82  181.17  565.88
#Mann= 3 , 0 , 0
       0      .1       0  105.62      .1       0  114.48      .1       0
Bank Sta=105.62,114.48
XS Rating Curve= 0 ,0
Exp/Cntr=0.3,0.1

Type RM Length L Ch R = 1 ,2194.526,93.64,91.41,91.58
XS GIS Cut Line= 3
     617656.5532    4332479.6378     617752.3285    4332519.9618
      617791.491    4332592.3506
#Sta/Elev= 30
       0  568.08    3.06  566.37   15.28  557.94   21.39  551.58   30.56  545.11
   36.68  542.04   39.73  539.47   45.85  536.24   61.13   528.6   64.18  527.52
   67.24  526.71    70.3  526.41   73.35  526.53   76.41  526.98   82.52  528.71
   91.69  531.74  100.86  534.05  103.92  535.22  106.97  536.14  113.06  537.39
  122.21  540.62   128.3  542.42  131.35  543.84   134.4  545.54  137.45  546.84
  143.55  548.61  167.93  559.23  174.03  562.98  177.08  563.65  186.22   566.8
#Mann= 3 , 0 , 0
       0      .1       0   67.24      .1       0   76.41      .1       0
Bank Sta=67.24,76.41
XS Rating Curve= 0 ,0
Exp/Cntr=0.3,0.1

Type RM Length L Ch R = 1 ,2103.12 ,49.2,49.2,49.2
XS GIS Cut Line= 3
     617621.7869    4332566.3155     617693.6359    4332595.5961
      617778.493    4332601.1605
#Sta/Elev= 30
       0  558.05    2.98  556.03    5.97  554.39    8.95   553.1   14.92  551.45
    17.9  550.41   20.89  549.05   23.87  546.97   26.86  545.55   38.79  540.61
   41.78  539.17   44.76  537.27   59.68  530.83   62.67  529.16   65.65  528.08
   71.62  527.75   83.66  527.44   89.73  526.91   95.81   525.5   98.85  525.06
  101.88  525.36  104.92  527.18  120.11  531.56  123.14  532.66  126.18  535.31
  141.37  544.75   144.4  548.04  147.44  550.37  153.51  553.85  162.63   558.3
#Mann= 3 , 0 , 0
       0      .1       0   95.81      .1       0  101.88      .1       0
Bank Sta=95.81,101.88
XS Rating Curve= 0 ,0
Exp/Cntr=0.3,0.1

Type RM Length L Ch R = 1 ,2054    ,42.2,42.2,42.2
XS GIS Cut Line= 4
617619.8651778644332579.67319527617681.4219074594332633.13035518
617721.9197558774332656.88909292617814.2548502684332658.50900686
#Sta/Elev= 30
       0 553.237   3.846 550.076  14.453 543.622  24.204 538.712  29.708 535.331
  31.357 534.512  34.066 534.658  36.045  534.14  42.783 530.799  50.111 527.572
  52.706  527.02  55.858 526.765   84.27 525.327  88.376  524.61  93.256 523.098
  95.502 522.484  97.749  522.42 101.573 522.751 111.227 523.085 119.799  523.78
 128.481 525.828 140.006 526.763 144.684 527.483 158.454 528.824 162.685  529.57
 177.793 531.044 183.052 532.143 189.202 532.849 201.501  535.26 220.831 537.414
#Mann= 3 , 0 , 0
       0      .1       0  93.256      .1       0 101.573      .1       0
Bank Sta=93.256,101.573
XS Rating Curve= 0 ,0
Exp/Cntr(USF)=0,0
Exp/Cntr=0.3,0.1

Type RM Length L Ch R = 1 ,2011.762,105.42,91.52,80.94
XS GIS Cut Line= 3
     617597.1806    4332588.5406     617688.3047    4332694.2456
     617740.0559    4332726.6533
#Sta/Elev= 30
       0  557.85    3.03  555.62    6.07  552.83    18.2  545.04   24.27  542.69
   30.34   538.2   33.37  535.39   42.47  528.37   48.54  524.98   54.61  523.51
   57.64  523.25   72.81  523.66   84.95  523.19   91.02  521.76   94.05   521.6
   97.09   520.8  100.12  519.98  103.15  519.89  106.19  520.27  121.36  523.72
  130.46  526.24  136.53  528.54  142.61  531.76  157.88  537.09  160.93  538.39
  163.98  540.42   182.3  547.47  185.36  549.98  191.46  552.85  200.62  558.35
#Mann= 3 , 0 , 0
       0      .1       0   97.09      .1       0  106.19      .1       0
Bank Sta=97.09,106.19
XS Rating Curve= 0 ,0
Exp/Cntr=0.3,0.1

Type RM Length L Ch R = 1 ,1920.24 ,78.96,91.44,97.97
XS GIS Cut Line= 5
     617539.2367    4332746.4971     617593.7921    4332747.7069
     617618.2713    4332735.1613     617637.5214     4332717.855
     617737.6746    4332733.0034
#Sta/Elev= 30
       0  557.06    3.03  553.86    9.09  548.78   15.16  543.37   18.19  541.03
   21.22  539.27   33.35   530.9   36.38  529.43   42.44  527.54   45.47  526.95
   51.54  526.29   57.63  524.64   60.68  523.44   63.74  521.69   66.79  519.52
   72.91  518.04   79.02  516.95   87.83  517.95   114.1   519.7  120.24  521.28
  132.52  523.04  141.73  526.35     154  529.62  166.28  533.96  172.42  536.49
  178.56  540.74  193.91  547.56  196.98  549.73  200.05  552.38  209.25   558.1
#Mann= 3 , 0 , 0
       0      .1       0   72.91      .1       0   87.83      .1       0
Bank Sta=72.91,87.83
XS Rating Curve= 0 ,0
Exp/Cntr=0.3,0.1

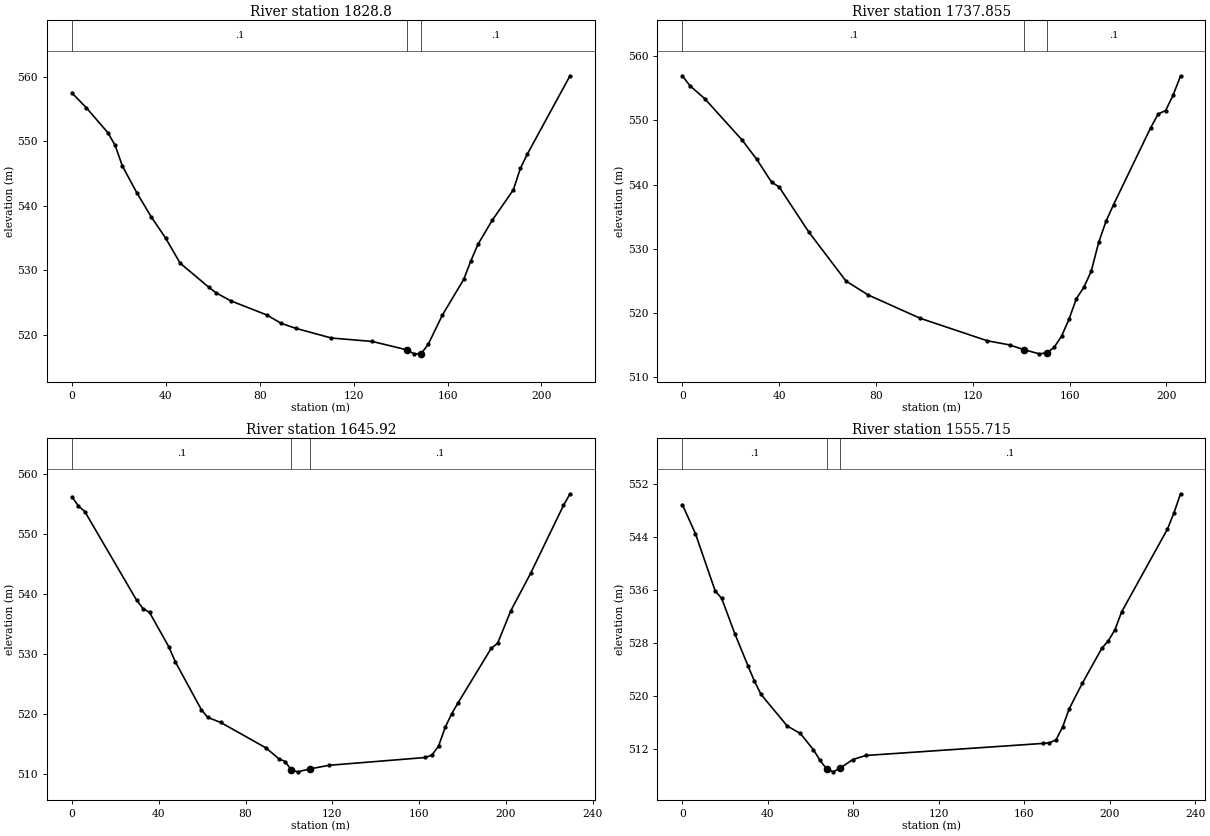
Type RM Length L Ch R = 1 ,1828.8  ,77.76,90.94,94.72
XS GIS Cut Line= 5
     617521.6331    4332757.5038     617614.8206    4332811.2019
      617637.899    4332814.4813     617646.3383    4332817.2117
     617712.1334    4332847.4623
#Sta/Elev= 30
       0  557.51    6.15   555.2   15.36  551.31   18.44  549.34   21.51  546.15
   27.66     542    33.8  538.26   39.95  534.95   46.09  531.08   58.39  527.31
   61.46  526.46    67.6  525.24   82.97  523.04   89.11  521.74   95.26  520.97
  110.47  519.46  127.95  518.92  142.75  517.61  145.77     517  148.78  517.02
   151.8  518.51  157.84  523.05  166.89  528.56  169.91  531.42  172.92  533.98
  178.96   537.7  188.01  542.45  191.03  545.81  194.04  548.05  212.15  560.16
#Mann= 3 , 0 , 0
       0      .1       0  142.75      .1       0  148.78      .1       0
Bank Sta=142.75,148.78
XS Rating Curve= 0 ,0
Exp/Cntr=0.3,0.1

Type RM Length L Ch R = 1 ,1737.855,84.18,91.93,97.68
XS GIS Cut Line= 2
     617517.3997    4332762.7955     617621.1166    4332940.5959
#Sta/Elev= 30
       0  556.93    3.07   555.4    9.22  553.37   24.58  546.97   30.72  543.93
   36.87  540.36   39.94  539.64   52.23  532.61   67.59  524.98   76.81   522.8
   98.31  519.17  125.96  515.68  135.18  515.03  141.32  514.27  147.47  513.64
  150.54  513.79  153.61  514.64  156.68  516.39  159.76  519.03  162.83  522.25
   165.9     524  168.97  526.53  172.05  531.02  175.12  534.35  178.19  536.88
  193.55  548.87  196.62  550.98   199.7  551.52  202.77  553.91  205.84  556.88
#Mann= 3 , 0 , 0
       0      .1       0  141.32      .1       0  150.54      .1       0
Bank Sta=141.32,150.54
XS Rating Curve= 0 ,0
Exp/Cntr=0.3,0.1

Type RM Length L Ch R = 1 ,1645.92 ,95.45,90.2,61.81
XS GIS Cut Line= 5
      617474.008    4332798.7789     617508.4455    4332884.5255
      617498.307    4332908.5377     617500.8246     4332931.614
     617553.3831    4333001.9793
#Sta/Elev= 30
       0  556.23    2.98  554.72    5.96  553.77   29.81     539   32.79  537.61
   35.77  536.96   44.71   531.2   47.69  528.71   59.62  520.78    62.6  519.47
   68.56  518.63   89.42  514.39    95.3   512.6    98.2  512.12  101.09  510.71
  103.99   510.4  109.78   510.9  118.47  511.49  162.88  512.79  165.91  513.21
  168.94  514.69  171.97  517.79     175  520.09  178.02  521.95  193.17  530.96
   196.2  531.85  202.25  537.26  211.34  543.46  226.48  554.78  229.51  556.73
#Mann= 3 , 0 , 0
       0      .1       0  101.09      .1       0  109.78      .1       0
Bank Sta=101.09,109.78
XS Rating Curve= 0 ,0
Exp/Cntr=0.3,0.1

Type RM Length L Ch R = 1 ,1555.715,95.46,92.73,76.18
XS GIS Cut Line= 2
     617371.3494     4332862.279     617530.6995    4333032.5299
#Sta/Elev= 30
       0  548.93    6.14  544.53   15.34  535.92   18.41  534.77   24.55  529.45
   30.68  524.62   33.75  522.27   36.82  520.28   49.09  515.51   55.23  514.38
   61.37  511.92   64.43  510.33    67.5  509.04   70.57  508.59   73.64   509.1
   79.78  510.45   85.91  511.06  168.76  512.88  171.82  512.98  174.89  513.41
  177.96  515.32  181.03  518.07  187.17  521.93  196.37  527.25  199.44  528.39
  202.51  530.05  205.58  532.71  227.05  545.22  230.12  547.68  233.19  550.57
#Mann= 3 , 0 , 0
       0      .1       0    67.5      .1       0   73.64      .1       0
Bank Sta=67.5,73.64
XS Rating Curve= 0 ,0
Exp/Cntr=0.3,0.1