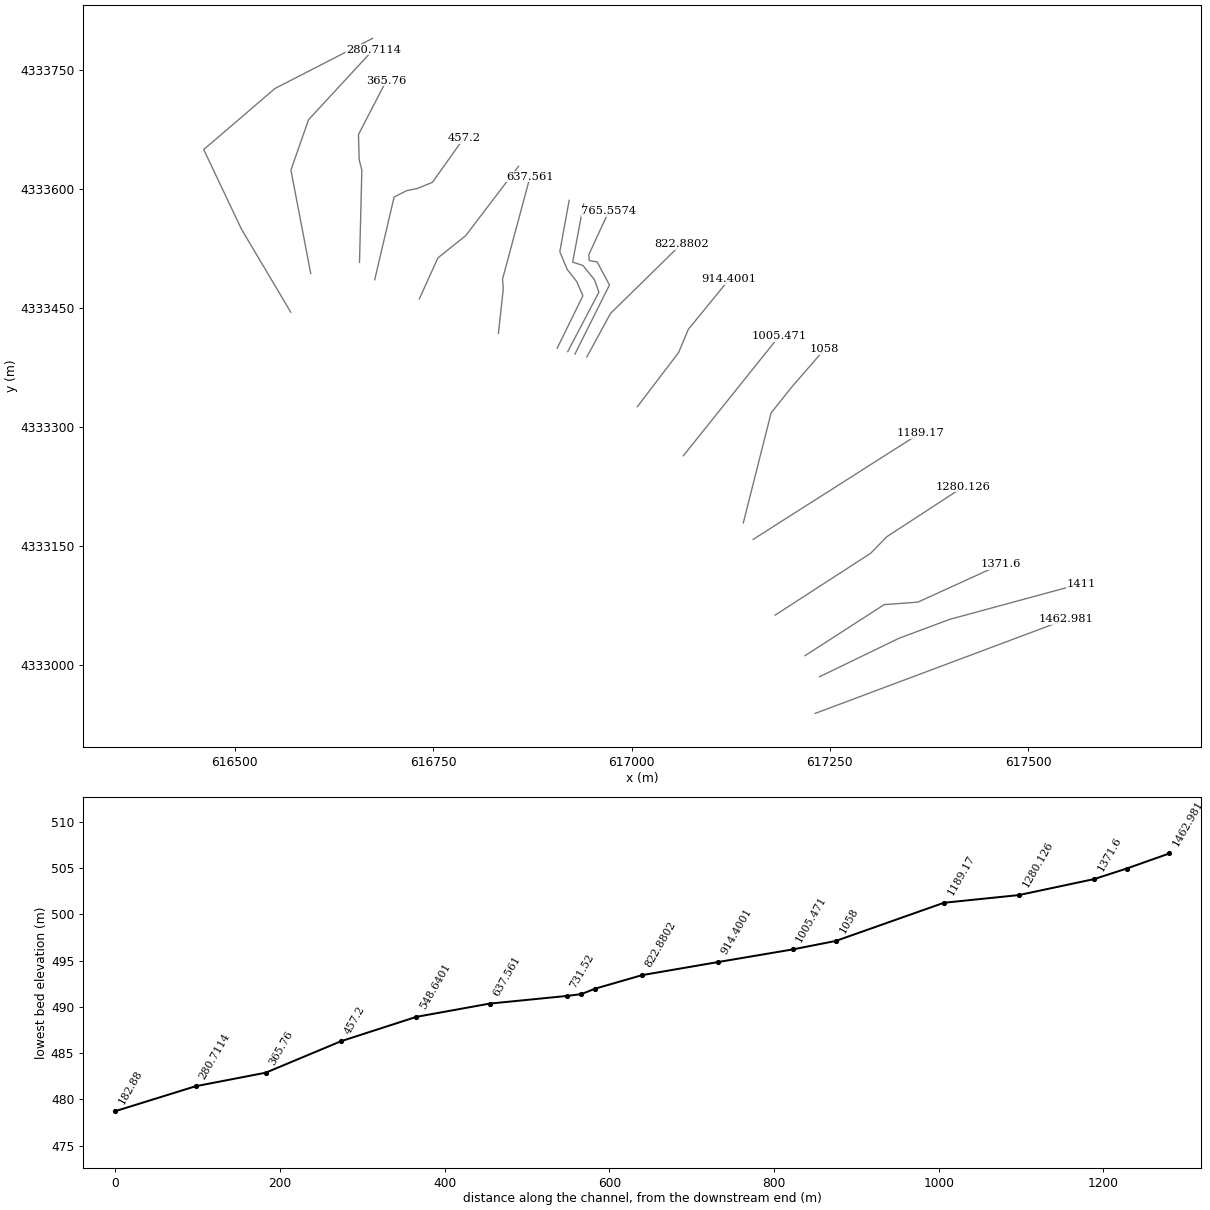
HEC-RAS study MillRun.prj: MillRun

--- MillRun.g01 (geometry) --- (continued)

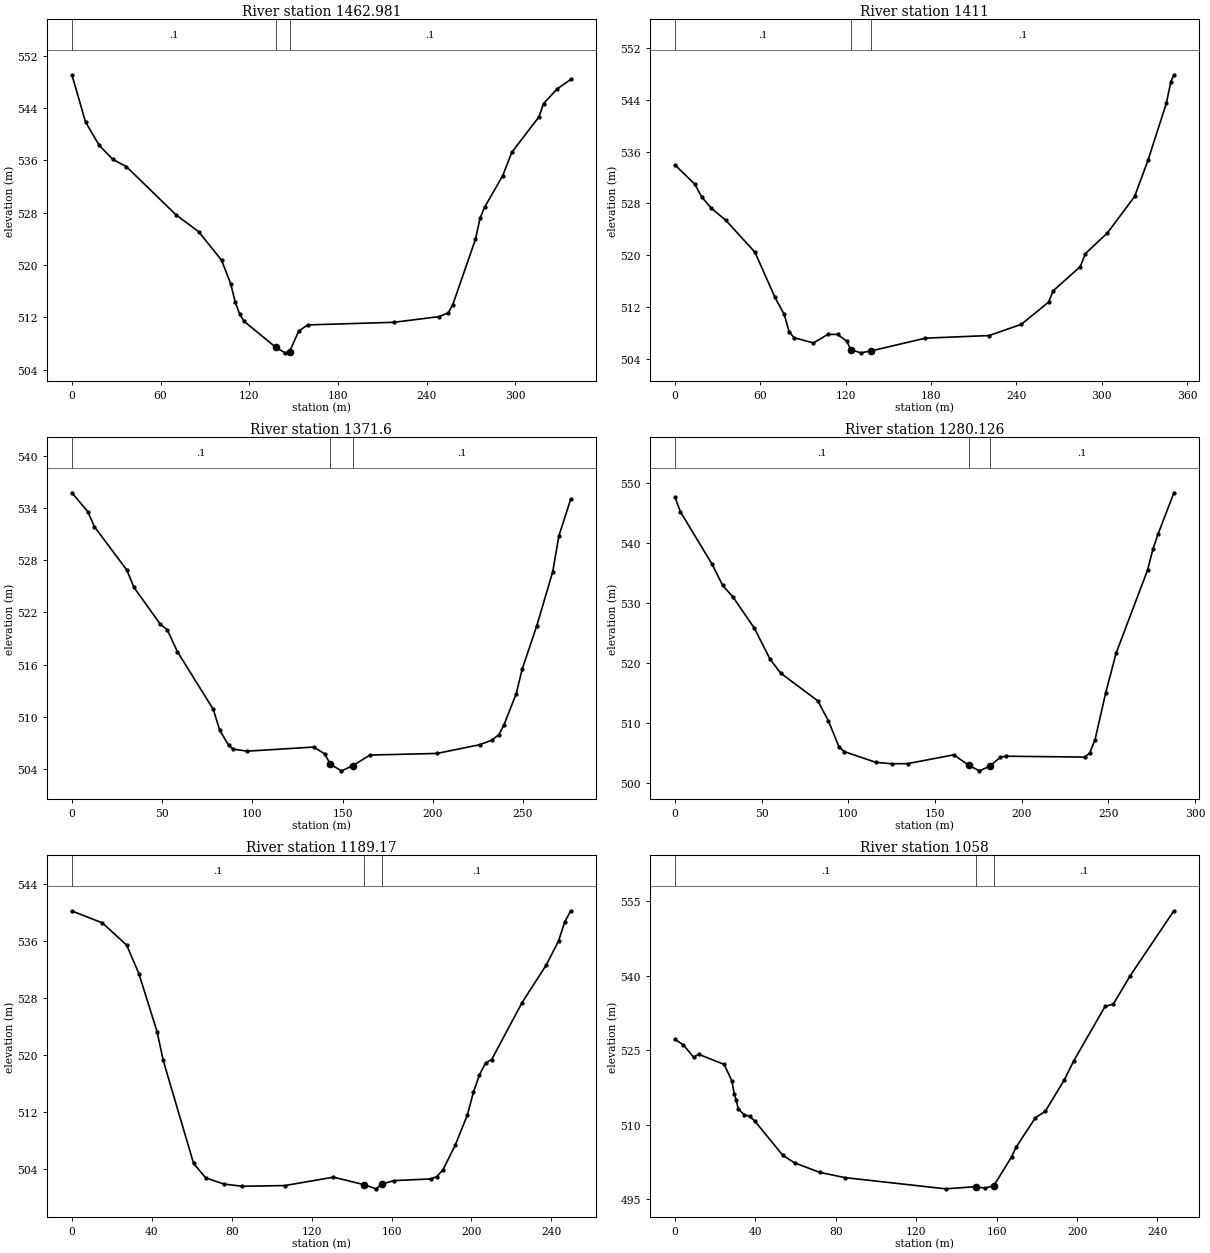
Type RM Length L Ch R = 1 ,1462.981,51.9,51.9,51.9
XS GIS Cut Line= 2
     617231.6492    4332938.4792     617547.6328    4333056.8716
#Sta/Elev= 30
       0  549.09     9.2  541.87   18.41  538.32   27.61  536.16   36.81  535.05
   70.55  527.65   85.89  525.06  101.23  520.73  107.37  517.17  110.43  514.37
   113.5  512.46  116.57  511.37  138.04  507.39  144.18  506.57  147.24  506.74
  153.38  509.89  159.51  510.84   217.8  511.24  248.47  512.11  254.61  512.69
  257.68  513.96  273.02  523.95  276.08  527.13  279.15  528.83  291.42  533.65
  297.56  537.23  315.96  542.66  319.03  544.68  328.23  546.92  337.44  548.37
#Mann= 3 , 0 , 0
       0      .1       0  138.04      .1       0  147.24      .1       0
Bank Sta=138.04,147.24
XS Rating Curve= 0 ,0
Exp/Cntr=0.3,0.1

Type RM Length L Ch R = 1 ,1411    ,39.5,39.5,39.5
XS GIS Cut Line= 4
 617237.025517494332984.65167944617337.4601815664333033.24909755
617401.1767964094333057.00783528617566.408017953 4333101.8254542
#Sta/Elev= 30
       0  533.93  13.808  530.98  18.698 529.008  25.528 527.246  35.774 525.376
  56.157 520.467  70.273 513.485  76.757 510.857  80.172 508.208  83.587  507.28
  97.248 506.464 107.494 507.786 114.217  507.78 120.779 506.726 123.413 505.447
 130.622 504.937 137.753 505.231 175.991 507.202  220.92 507.609 243.537 509.347
 262.649 512.768 265.834 514.501 284.946 518.256 288.574 520.263 304.059 523.454
 323.171 529.078 332.727 534.774 345.468 543.467 348.654 546.822 350.778 547.861
#Mann= 3 , 0 , 0
       0      .1       0 123.413      .1       0 137.753      .1       0
Bank Sta=123.413,137.753
XS Rating Curve= 0 ,0
Exp/Cntr(USF)=0,0
Exp/Cntr=0.3,0.1

Type RM Length L Ch R = 1 ,1371.6  ,73.87,91.47,97.69
XS GIS Cut Line= 4
617218.7927644824333011.23087928     617318.5647    4333075.5797
     617361.0569    4333078.7272617465.8314213544333126.48477902
#Sta/Elev= 30
       0 535.754     8.8 533.587  12.458 531.866  30.503 526.845  34.407 524.872
   49.04 520.634   52.81 520.024  58.482 517.488  78.306 510.878  81.964 508.448
  86.842 506.747  89.281 506.296   97.22  506.06 133.988 506.532 140.153 505.745
 143.236 504.545 149.401 503.799 155.566 504.375 165.149 505.612 202.313 505.798
 225.963 506.798  232.72  507.32 236.722 507.968 239.477 509.077 246.235  512.64
 249.613 515.516 257.608 520.428 266.506 526.689 269.885 530.776 276.477 535.028
#Mann= 3 , 0 , 0
       0      .1       0 143.236      .1       0 155.566      .1       0
Bank Sta=143.236,155.566
XS Rating Curve= 0 ,0
Exp/Cntr=0.3,0.1

Type RM Length L Ch R = 1 ,1280.126,95.65,90.96,90.27
XS GIS Cut Line= 4
     617181.1313     4333062.375     617301.3879    4333140.2274
     617321.8317    4333161.1652     617418.3836    4333224.0886
#Sta/Elev= 30
       0  547.65    3.05  545.25   21.34   536.5   27.43  532.98   33.53  530.99
   45.72  525.84   54.86  520.64   60.96  518.34    82.3  513.74   88.39  510.43
   94.49  506.12   97.54  505.28  115.82  503.49  124.97  503.25  134.11  503.27
  160.82  504.74  169.59  502.96  175.55  502.07  181.62  502.85  187.68  504.35
  190.72  504.51  236.21  504.36  239.24  505.04  242.27  507.27  248.34  514.96
  254.41  521.66   272.6  535.55  275.64  538.99  278.67  541.56  287.77  548.41
#Mann= 3 , 0 , 0
       0      .1       0  169.59      .1       0  181.62      .1       0
Bank Sta=169.59,181.62
XS Rating Curve= 0 ,0
Exp/Cntr=0.3,0.1

Type RM Length L Ch R = 1 ,1189.17 ,131.1,131.1,131.1
XS GIS Cut Line= 2
     617153.3037    4333157.7773     617363.9652    4333291.8347
#Sta/Elev= 30
       0  540.24   15.23  538.57   27.41  535.45    33.5  531.46   42.63   523.3
   45.68  519.29    60.9  504.81   66.99  502.78   76.13  501.91   85.26   501.6
  106.58   501.7  130.94  502.88  146.17  501.83  152.26  501.24   155.3  501.92
  161.39   502.4  179.66  502.63  182.71  502.97  185.75  503.91  191.84  507.35
  197.93  511.58  200.98  514.79  204.02  517.25  207.07   518.9  210.11  519.38
  225.34  527.38  237.52  532.69  243.61  536.03  246.65  538.68   249.7  540.27
#Mann= 3 , 0 , 0
       0      .1       0  146.17      .1       0   155.3      .1       0
Bank Sta=146.17,155.3
XS Rating Curve= 0 ,0
Exp/Cntr=0.3,0.1

Type RM Length L Ch R = 1 ,1058    ,52.6,52.6,52.6
XS GIS Cut Line= 4
617140.9106239134333178.50138054617176.0087592084333317.27400778
617201.387410883 4333349.1323152617243.505173237 4333397.7297333
#Sta/Elev= 30
       0 527.202    4.15  526.06   9.198  523.63  11.743  524.19  24.398 522.164
  28.225 518.885   29.46 516.123  30.399 515.035  31.396 513.238  34.341 512.028
  37.052 511.717  39.583 510.793  53.594  503.87  59.417 502.354  71.955 500.441
  84.493 499.382 134.645 497.123   149.5 497.557 154.263 497.267 158.638 497.791
 167.389 503.543 169.715 505.525 179.271 511.437 184.188 512.713 193.577 518.997
 198.271 522.821 213.969 533.855 218.037 534.283 226.435 540.003 248.182 553.074
#Mann= 3 , 0 , 0
       0      .1       0   149.5      .1       0 158.638      .1       0
Bank Sta=149.5,158.638
XS Rating Curve= 0 ,0
Exp/Cntr(USF)=0,0
Exp/Cntr=0.3,0.1

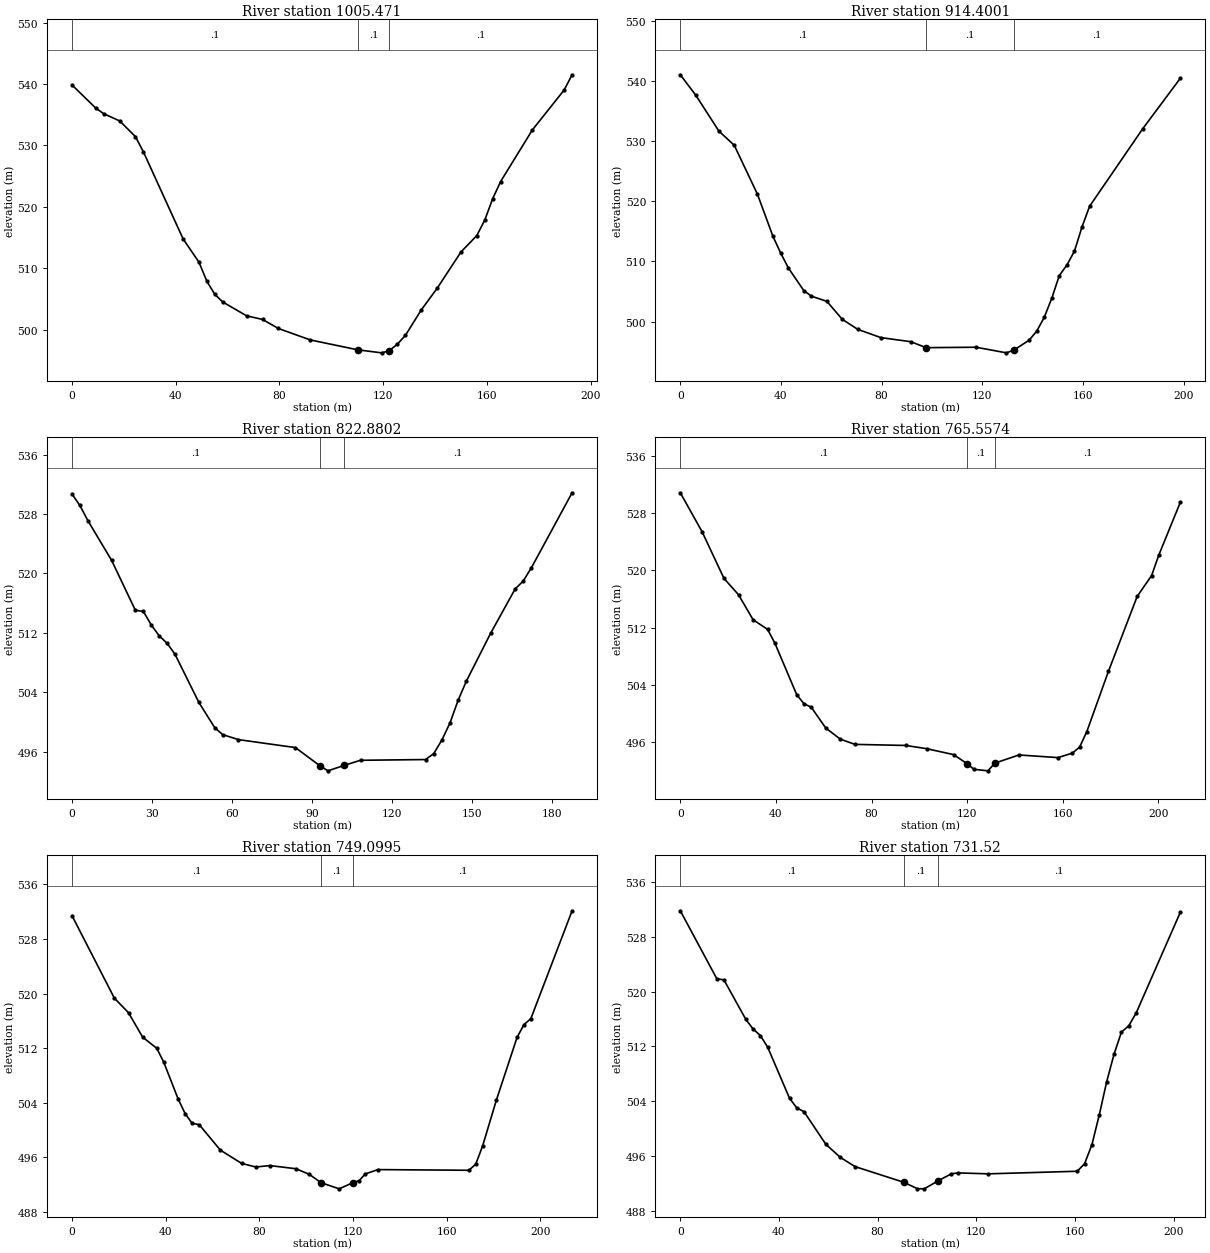
Type RM Length L Ch R = 1 ,1005.471,88.53,91.07,93.6
XS GIS Cut Line= 2
     617065.3295     4333263.214     617185.9484    4333413.7232
#Sta/Elev= 30
       0  539.84    9.18  536.07   12.25  535.15   18.37  533.99   24.49  531.42
   27.55  528.94   42.86  514.76   48.98  510.96   52.05  507.83   55.11  505.71
   58.17  504.48   67.35  502.23   73.48  501.64    79.6  500.17   91.85  498.31
  110.22  496.69   119.4   496.2  122.23  496.52  125.52  497.62  128.59  499.04
  134.71  503.19  140.83  506.71  150.02  512.63  156.14  515.31   159.2  517.83
  162.26  521.32  165.32  524.11  177.57  532.52  189.82  539.02  192.88   541.5
#Mann= 3 , 0 , 0
       0      .1       0  110.22      .1       0  122.23      .1       0
Bank Sta=110.22,122.23
XS Rating Curve= 0 ,0
Exp/Cntr=0.3,0.1

Type RM Length L Ch R = 1 ,914.4001,95.72,91.52,85.83
XS GIS Cut Line= 4
     617007.3857    4333325.1266     617059.4145    4333393.3964
     617071.6329    4333422.6465     617123.0644    4333485.4913
#Sta/Elev= 30
       0  541.01    6.13  537.63   15.33  531.66   21.46  529.29   30.66  521.17
   36.79   514.2   39.85  511.44   42.92  508.94   49.05  505.18   52.11  504.24
   58.25  503.38   64.38  500.39   70.51  498.73    79.7  497.36    91.6  496.68
   97.69  495.69  117.54  495.76  129.57  494.83  132.57  495.29  138.59  496.92
   141.6  498.41   144.6   500.7  147.61  503.88  150.62  507.67  153.63  509.41
  156.64  511.73  159.64  515.75  162.65  519.17   183.7  532.01  198.74  540.45
#Mann= 3 , 0 , 0
       0      .1       0   97.69      .1       0  132.57      .1       0
Bank Sta=97.69,132.57
XS Rating Curve= 0 ,0
Exp/Cntr=0.3,0.1

Type RM Length L Ch R = 1 ,822.8802,23.72,57.32,74.37
XS GIS Cut Line= 3
     616943.7197    4333387.8536     616973.5238    4333442.6549
      617062.816    4333530.1791
#Sta/Elev= 30
       0  530.68    2.97  529.14    5.94  527.11   14.85  521.76   23.76  515.03
   26.74  514.89   29.71  513.06   32.68   511.6   35.65   510.6   38.62  509.11
   47.53  502.65   53.47  499.25   56.44  498.31   62.38  497.63   83.73  496.56
   92.88  494.12   95.93  493.43  102.03  494.17  108.13  494.85  132.52  494.95
  135.57  495.75  138.62  497.57  141.67  499.88  144.72  502.94  147.77  505.48
  156.92  511.96  166.07   517.9  169.12  518.98  172.17  520.76  187.42  530.85
#Mann= 3 , 0 , 0
       0      .1       0   92.88      .1       0  102.03      .1       0
Bank Sta=92.88,102.03
XS Rating Curve= 0 ,0
Exp/Cntr=0.3,0.1

Type RM Length L Ch R = 1 ,765.5574,20.88,16.46,20.86
XS GIS Cut Line= 6
     616928.6947    4333391.4166     616972.2187    4333478.5459
     616956.6744    4333507.6501     616946.7525    4333509.3038
      616946.091    4333516.5798     616971.3888    4333571.2537
#Sta/Elev= 30
       0  530.85    9.13  525.39   18.26  518.88   24.35  516.59   30.44   513.1
   36.52  511.74   39.57  509.82    48.7  502.61   51.74  501.34   54.78  500.86
   60.87  497.94   66.96  496.39   73.05  495.66   94.35  495.51  103.04  495.06
  114.32  494.23  119.97  492.96  122.88  492.17  128.71  491.96  131.62  493.04
  141.68  494.18  158.02  493.81  164.04  494.44  167.06  495.28  170.07  497.44
   179.1  505.86  191.15  516.36  197.18  519.27  200.19  522.14  209.23  529.55
#Mann= 3 , 0 , 0
       0      .1       0  119.97      .1       0  131.62      .1       0
Bank Sta=119.97,131.62
XS Rating Curve= 0 ,0
Exp/Cntr=0.3,0.1

Type RM Length L Ch R = 1 ,749.0995,21.31,17.58,11.99
XS GIS Cut Line= 6
     616919.6033    4333394.5427     616958.8837    4333469.3869
     616953.2612    4333485.2619     616938.7091    4333503.1213
     616925.8107    4333507.4208      616939.564      4333580.45
#Sta/Elev= 30
       0  531.42   18.11  519.32   24.15  517.19   30.19  513.61   36.23  511.97
   39.24  509.91   45.28   504.6    48.3  502.42   51.32  500.98   54.34  500.79
   63.39  497.05   72.45  495.11   78.49  494.58   84.53  494.79   95.75  494.32
  101.37   493.5  106.47  492.27  114.13  491.38   120.1   492.3  122.68  492.58
  125.27  493.57  130.71   494.2  169.55   494.1  172.48  495.01  175.42  497.69
   181.3  504.42  190.11  513.57  193.05  515.45  195.98  516.31  213.61  532.13
#Mann= 3 , 0 , 0
       0      .1       0  106.47      .1       0   120.1      .1       0
Bank Sta=106.47,120.1
XS Rating Curve= 0 ,0
Exp/Cntr=0.3,0.1

Type RM Length L Ch R = 1 ,731.52  ,98.67,93.96,76.09
XS GIS Cut Line= 6
     616906.2548    4333398.6775     616938.7305    4333464.9456
     616930.9334    4333482.9161      616919.016    4333497.9826
     616909.6263    4333520.5083     616921.4072    4333585.2106
#Sta/Elev= 30
       0   531.8   14.76   521.9   17.71  521.69   26.57  515.93   29.52  514.53
   32.47  513.57   35.42  511.88   44.28  504.41   47.23  503.01   50.18  502.44
   59.04  497.67   64.94  495.76   70.85  494.43   90.59  492.14   96.13   491.2
   98.88  491.18  104.36  492.31  109.85  493.37   112.6  493.51   124.8  493.37
  160.92  493.75  163.91  494.85   166.9  497.64  169.88     502  172.87  506.82
  175.86  510.85  178.85  514.07  181.84     515  184.83  516.87  202.77  531.61
#Mann= 3 , 0 , 0
       0      .1       0   90.59      .1       0  104.36      .1       0
Bank Sta=90.59,104.36
XS Rating Curve= 0 ,0
Exp/Cntr=0.3,0.1

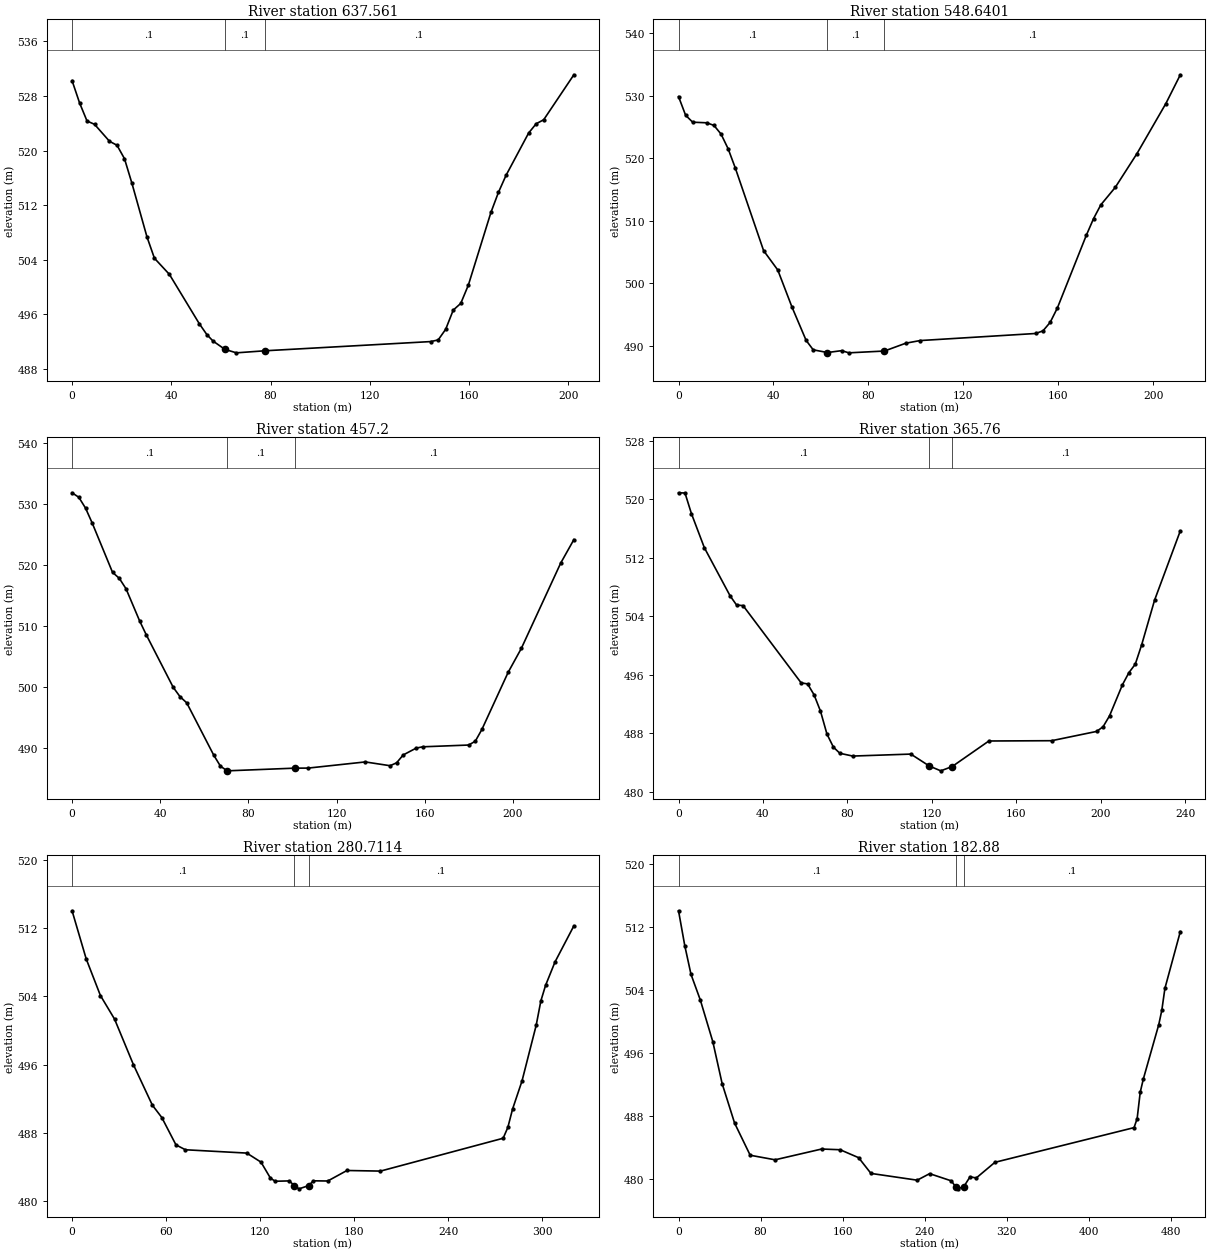
Type RM Length L Ch R = 1 ,637.561 ,92.66,88.92,64.98
XS GIS Cut Line= 5
     616832.2393    4333417.6045     616838.1522    4333471.5816
     616838.1522    4333476.5558     616837.3572    4333485.7633
     616872.0951    4333614.8459
#Sta/Elev= 30
       0  530.25    3.02  526.99    6.03  524.33    9.05  523.85   15.08  521.36
    18.1  520.78   21.12  518.81   24.13  515.19   30.17  507.36   33.18  504.22
   39.22  501.85   51.28  494.61    54.3  493.03   56.79  492.08   61.58  490.86
   66.21  490.35   77.63  490.65  144.47     492  147.51  492.24  150.54   493.8
  153.58  496.61  156.62   497.6  159.66  500.26  168.77  510.93  171.81  513.88
  174.85  516.36  183.96  522.57     187  523.93  190.04  524.52  202.19  531.11
#Mann= 3 , 0 , 0
       0      .1       0   61.58      .1       0   77.63      .1       0
Bank Sta=61.58,77.63
XS Rating Curve= 0 ,0
Exp/Cntr=0.3,0.1

Type RM Length L Ch R = 1 ,548.6401,93.84,91.44,82.39
XS GIS Cut Line= 4
     616732.5048    4333460.9736     616755.9288    4333512.6709
     616791.0991    4333540.8071     616857.4978    4333628.1095
#Sta/Elev= 30
       0  529.84    2.99  526.85    5.97  525.75   11.95  525.65   14.94  525.23
   17.92  523.85   20.91   521.5    23.9  518.46   35.85  505.24   41.82  502.15
   47.79  496.25   53.77  490.91   56.76   489.4   62.76  488.97   68.77  489.27
   71.77  488.92   86.78  489.21   95.79  490.46   101.8  490.88  150.54  492.01
  153.59  492.43  156.64  493.79  159.68   496.1  171.87   507.7  174.92  510.36
  177.97  512.55  184.06  515.34   193.2  520.73  205.39  528.73  211.48  533.32
#Mann= 3 , 0 , 0
       0      .1       0   62.76      .1       0   86.78      .1       0
Bank Sta=62.76,86.78
XS Rating Curve= 0 ,0
Exp/Cntr=0.3,0.1

Type RM Length L Ch R = 1 ,457.2   ,61.57,91.44,106.63
XS GIS Cut Line= 6
     616676.3031    4333485.1998     616700.7373    4333589.4323
      616716.717     4333597.501     616729.8272    4333600.0885
     616749.0239    4333607.9532     616788.7512    4333663.7939
#Sta/Elev= 30
       0  531.87    3.06  531.13    6.12  529.35    9.18  526.87   18.35  518.83
   21.41  517.85   24.47  516.14   30.59  510.91   33.65  508.59   45.88  499.98
   48.94  498.46      52  497.44   64.23  488.88   67.29  487.06   70.35  486.29
  100.94  486.73  107.06  486.74  132.98  487.75  144.25  487.13  147.21  487.61
  150.18  488.89   156.1  490.02  159.07  490.23  179.92  490.52   182.9  491.15
  185.88  493.07   197.8  502.44  203.76  506.35  221.64  520.35   227.6  524.19
#Mann= 3 , 0 , 0
       0      .1       0   70.35      .1       0  100.94      .1       0
Bank Sta=70.35,100.94
XS Rating Curve= 0 ,0
Exp/Cntr=0.3,0.1

Type RM Length L Ch R = 1 ,365.76  ,88.95,85.05,71.3
XS GIS Cut Line= 5
     616657.1115    4333507.1905      616660.079    4333623.2984
     616656.7207    4333636.3442     616655.8132    4333668.2012
     616690.8449     4333735.875
#Sta/Elev= 30
       0   520.9    3.06  520.87    6.11  518.05   12.23  513.39   24.45   506.8
   27.51  505.55   30.56  505.48   58.07  494.92   61.13  494.77   64.19  493.29
   67.24  491.05    70.3  487.92   73.36  486.13   76.41  485.29   82.52  484.91
  110.03  485.18  118.84  483.54  124.23  482.89  129.62  483.48     147  486.97
  176.73  487.01  198.06  488.28  201.11  488.92  204.16  490.41  210.26  494.65
  213.31   496.3  216.35  497.47   219.4  500.14   225.5  506.23  237.69   515.7
#Mann= 3 , 0 , 0
       0      .1       0  118.84      .1       0  129.62      .1       0
Bank Sta=118.84,129.62
XS Rating Curve= 0 ,0
Exp/Cntr=0.3,0.1

Type RM Length L Ch R = 1 ,280.7114,129.39,97.83,68.44
XS GIS Cut Line= 4
      616595.605    4333493.1374     616570.6579    4333623.4036
     616592.8829    4333686.9037     616674.5765    4333775.2922
#Sta/Elev= 30
       0  514.02    9.04  508.37   18.09  504.09   27.13  501.32   39.19  495.97
   51.24  491.24   57.27  489.79   66.32  486.58   72.35  486.01  111.53  485.62
  120.58  484.56   126.6  482.69  129.62  482.32  138.75  482.36  141.81   481.8
  144.87  481.43  150.98  481.81  154.04  482.37  163.21  482.35  175.45  483.58
  196.85  483.51  275.14  487.36  278.14  488.63  281.15  490.78  287.17  494.07
   296.2  500.58  299.21  503.46  302.22  505.28  308.23  508.02  320.27  512.25
#Mann= 3 , 0 , 0
       0      .1       0  141.81      .1       0  150.98      .1       0
Bank Sta=141.81,150.98
XS Rating Curve= 0 ,0
Exp/Cntr=0.3,0.1

Type RM Length L Ch R = 1 ,182.88  ,60.89,182.88,209.37
XS GIS Cut Line= 5
     616570.4695    4333444.1893     616508.3811     4333548.716
     616460.7086     4333649.247     616550.5131    4333726.2222
     616673.6572    4333789.4713
#Sta/Elev= 30
       0  514.07    6.08  509.64   12.16  505.99   21.28  502.72   33.43  497.44
   42.55   492.1   54.71  487.08   69.91     483   94.22  482.42  139.62  483.79
  157.66   483.7   175.7  482.69  187.73  480.69  232.84  479.83  244.97  480.66
   266.2  479.74  270.66  478.93  272.26  478.73  278.33  479.01   284.4  480.26
  290.46  480.11  308.66   482.1  444.41  486.51  447.42  487.66  450.43  491.01
  453.44  492.68  468.49  499.59   471.5  501.43  474.51  504.21  489.55  511.43
#Mann= 3 , 0 , 0
       0      .1       0  270.66      .1       0  278.33      .1       0
Bank Sta=270.66,278.33
XS Rating Curve= 0 ,0
Exp/Cntr=0.3,0.1
LCMann Table=0

Chan Stop Cuts=-1
Use User Specified Reach Order=0
Composite Channel Slope=5